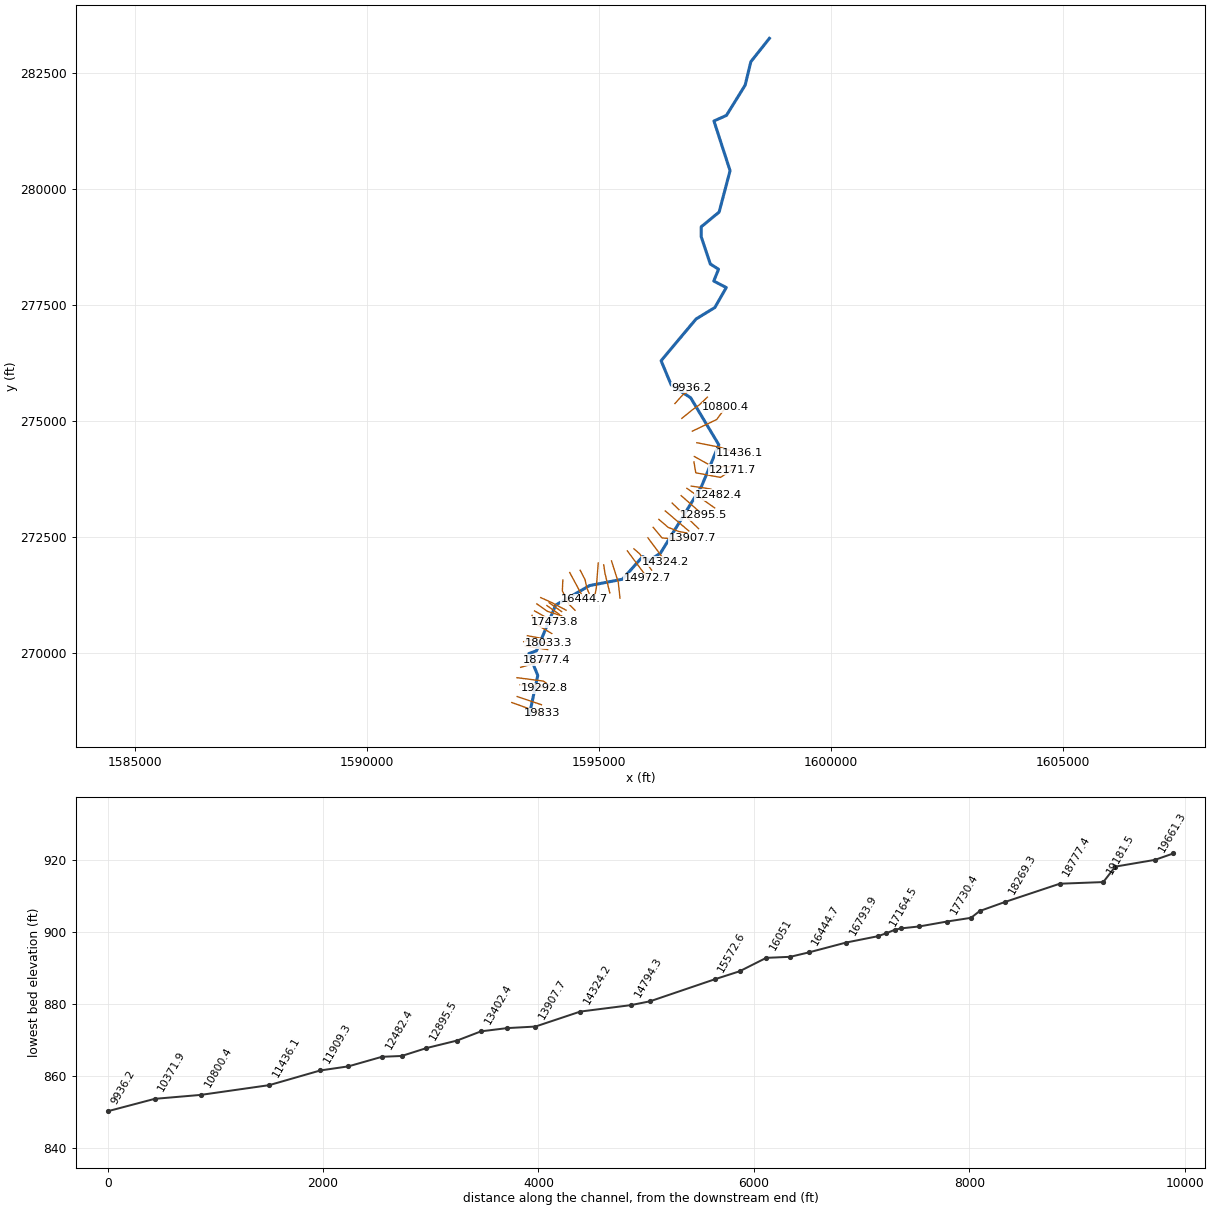
--- RFKRNLDCK.prj (project) ---

Proj Title=RFKRNLDCK
Current Plan=p01
Default Exp/Contr=0,0
English Units
Geom File=g01
Flow File=f01
Plan File=p01
BEGIN DESCRIPTION:
END DESCRIPTION:
DSS Export Rating Curves= 0
DSS Export Rating Curve Sorted= 0
DSS Export Volume Flow Curves= 0
DXF OffsetX= 0
DXF OffsetY= 0
DXF ScaleX= 0
DXF ScaleY= 0

--- RFKRNLDCK.p01 (plan) ---

Plan Title=Floodplain
Program Version=4.00
Geom File=g01
Flow File=f01
K Sum by GR=0
Std Step Tol=0.01
Critical Tol=0.01
Num of Std Step Trials=20
Max Error Tol=0.3
Flow Tol Ratio=0.001
Split Flow NTrial=30
Split Flow Tol=0.02
Split Flow Ratio=0.02
Log Output Level=0
Friction Slope Method=1
Unsteady Friction Slope Method=2
Unsteady Bridges Friction Slope Method=1
Global Log Level=0
CheckData=False
Run HTab=0
Run UNet=0
Run PostProcess=0
UNET Theta=0
UNET Theta Warmup=0
UNET ZTol=0
UNET ZSATol=0
UNET MxIter=0
UNET MaxInSteps=0
UNET DtIC=0
UNET DtMin=0
UNET MaxCRTS=0
UNET WFStab=0
UNET SFStab=0
UNET WFX=0
UNET SFX=0
UNET DSS MLevel=0
UNET DZMax Abort=0
UNET Convert EG Bridges=0
UNET Use Existing IB Tables=0
UNET Froude Limit=0
UNET Froude Power=0
Write IC File=0
Echo Input=False
Echo Output=False
Write Detailed=0

--- RFKRNLDCK.f01 (steady flow) ---

Flow Title=NFF Regression Equation
Program Version=4.10
Number of Profiles= 1
Profile Names=P100yr
River Rch & RM=RFKRNLDCK,Main            ,19833
559.3673
River Rch & RM=RFKRNLDCK,Main            ,17730.4
595.1413
River Rch & RM=RFKRNLDCK,Main            ,17473.8
736.9852
River Rch & RM=RFKRNLDCK,Main            ,16444.7
811.6333
River Rch & RM=RFKRNLDCK,Main            ,16051
834.6367
River Rch & RM=RFKRNLDCK,Main            ,13907.7
922.6489
River Rch & RM=RFKRNLDCK,Main            ,13645.8
1043.482
River Rch & RM=RFKRNLDCK,Main            ,12171.7
1059.598
River Rch & RM=RFKRNLDCK,Main            ,11909.3
1180.484
River Rch & RM=RFKRNLDCK,Main            ,10800.4
 1227.21
River Rch & RM=RFKRNLDCK,Main            ,8884.7
1326.516
River Rch & RM=RFKRNLDCK,Main            ,6682.6
1413.046
River Rch & RM=RFKRNLDCK,Main            ,453.7
1557.949
River Rch & RM=RFKRNLDCK,Main            ,84.3
1560.327
Boundary for River Rch & Prof#=RFKRNLDCK,Main            , 1
Up Type= 0
Dn Type= 3
Dn Slope=0.00279
DSS Import GetInterval= 0
DSS Import GetPeak= 0
DSS Import FillOption= 0

--- RFKRNLDCK.g01 (geometry) ---

Geom Title=USGS 10m DEM
Program Version=4.10

River Reach=RFKRNLDCK       ,Main
Reach XY= 30
     1593509.054      268701.735     1593682.789      269514.174
     1593490.521      269985.576     1593654.996      270045.189
     1594068.194      271030.794      1594800.58      271452.804
     1595508.699       271589.57     1595944.285      272079.239
     1596085.001       271995.56     1596327.151      272151.822
     1597212.474      273594.172     1597584.723      274488.465
     1596978.012      275502.362     1596557.658      275780.339
     1596340.701      276302.392     1597093.271      277201.408
     1597498.709      277449.553     1597745.498      277879.399
     1597475.658      278020.421     1597578.712      278275.346
     1597401.079      278387.893     1597205.817      278973.677
     1597205.817      279190.634     1597590.916      279507.934
     1597827.005      280400.197     1597479.719      281472.761
     1597748.943      281593.551     1598151.714      282244.785
     1598274.827      282751.346     1598674.831      283255.496

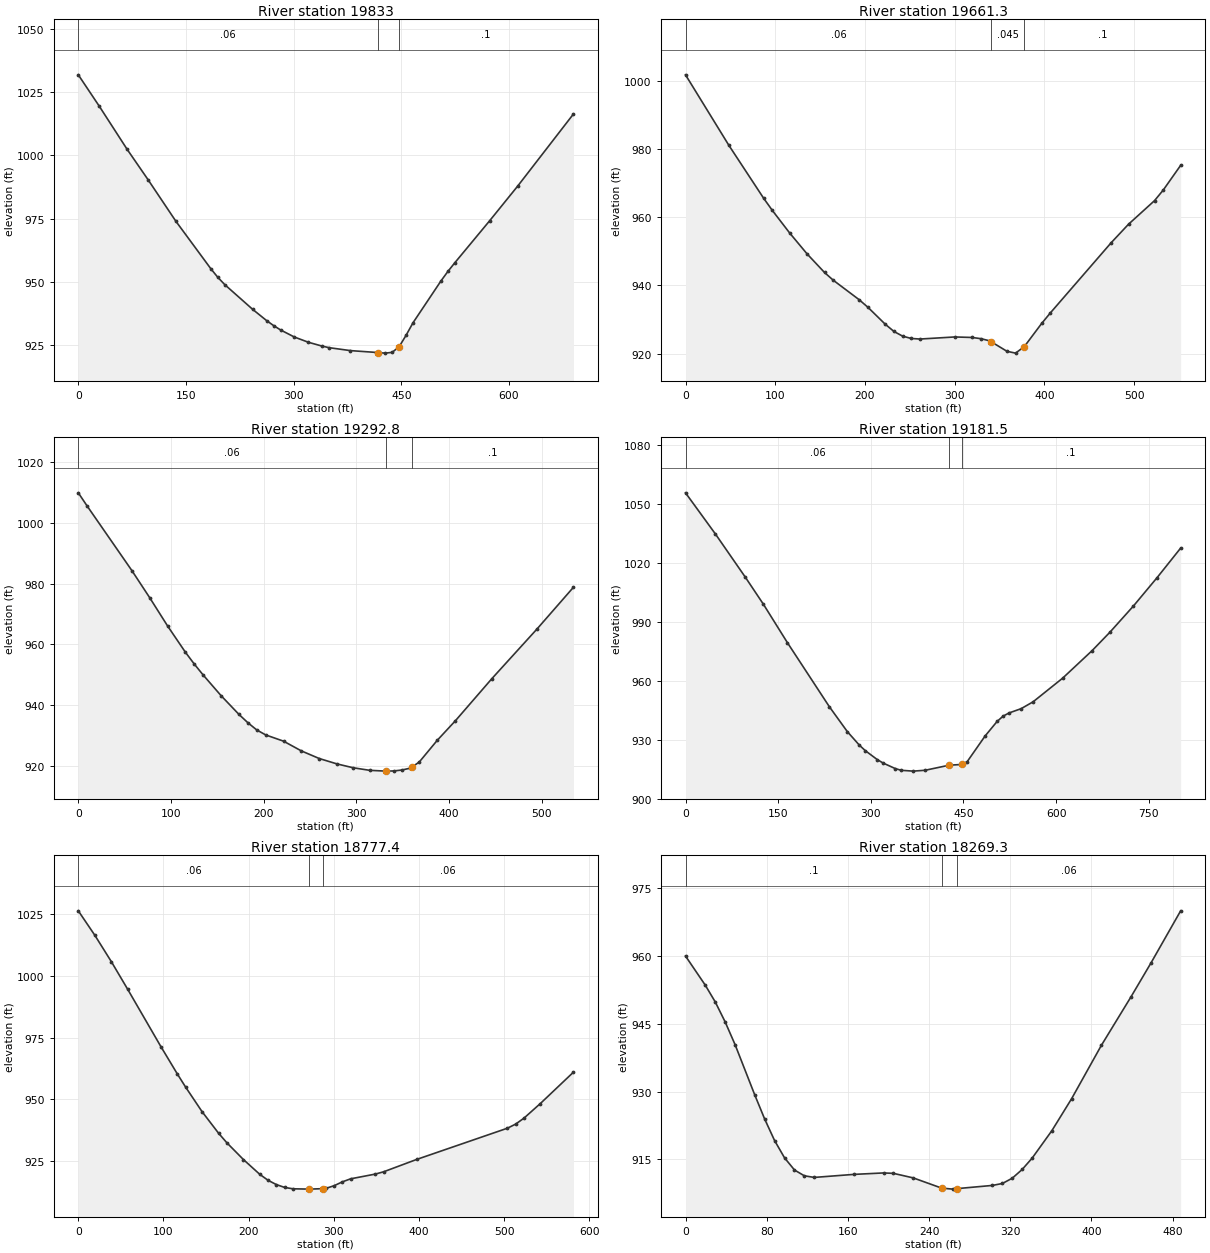
Type RM Length L Ch R = 1 ,19833   ,171,171.6,172.1
XS GIS Cut Line= 2
     1593122.975      268930.346     1593771.847      268695.971
#Sta/Elev= 30
       0 1031.81    29.2 1019.43      68 1002.41    97.2   990.4     136  973.98
   184.6  955.27   194.3  951.88   204.1  948.96   242.9  939.22   262.4  934.76
   272.1   932.8   281.8  931.08   301.2  928.26   320.7   926.2   340.1  924.66
   349.8  924.06     379  922.92   417.8  922.14   427.6  921.92   437.3  922.22
   446.5  924.33     447  924.44   456.7  928.96   466.4  933.92   505.3  950.42
     515  954.19   524.7  957.63   573.3  974.24   612.2  987.87   689.9 1016.34
#Mann= 3 , 0 , 0
       0     .06       0   417.8    .045       0   446.5      .1       0
Bank Sta=417.8,446.5
XS Rating Curve= 0 ,0
Exp/Cntr=0.3,0.1

Type RM Length L Ch R = 1 ,19661.3 ,360,368.6,368.1
XS GIS Cut Line= 2
     1593240.163      269058.384     1593763.166      268882.603
#Sta/Elev= 30
       0  1001.7    48.4     981    87.1  965.51    96.8  961.94   116.2   955.3
   135.5  949.21   154.9  943.77   164.6  941.51   193.6  935.77   203.3  933.56
   222.6   928.6   232.3  926.48     242   925.1   251.7  924.42   261.4  924.26
   300.1  924.87   319.4  924.72   329.1  924.37   338.8  923.75   340.7  923.46
   358.2  920.67   367.8  920.13   377.5  922.02   396.9  928.83   406.6  931.92
   474.3  952.47   493.7  957.91   522.7  964.83   532.4  967.93   551.8  975.17
#Mann= 3 , 0 , 0
       0     .06       0   340.7    .045       0   377.5      .1       0
Bank Sta=340.7,377.5
XS Rating Curve= 0 ,0
Exp/Cntr=0.3,0.1

Type RM Length L Ch R = 1 ,19292.8 ,115.1,111.3,116
XS GIS Cut Line= 4
     1593301.329      269312.909     1593580.161      269296.173
     1593658.927      269299.127     1593824.876      269239.778
#Sta/Elev= 30
       0    1010     9.6 1005.63    57.8  984.38    77.1  975.41    96.3  966.14
   115.6  957.45   125.2  953.54   134.8  949.93   154.1  943.13   173.4  936.95
     183  934.21   192.6  931.83   202.3  930.18   221.5  928.13   240.8  924.91
   260.1   922.4   279.3  920.62   296.8  919.35   314.4  918.52   331.9  918.25
   340.6  918.31   349.4  918.62   358.2  919.23  360.46  919.66     368  921.25
   387.5  928.44   407.1  934.89   446.3  948.72   495.2  965.15   534.4  978.86
#Mann= 3 , 0 , 0
       0     .06       0   331.9    .045       0  360.46      .1       0
Bank Sta=331.9,360.46
XS Rating Curve= 0 ,0
Exp/Cntr=0.3,0.1

Type RM Length L Ch R = 1 ,19181.5 ,390.9,404.2,412.8
XS GIS Cut Line= 3
     1593235.823       269465.61     1593803.531      269392.694
     1593988.427      269257.277
#Sta/Elev= 30
       0 1055.54    48.5 1034.56      97 1012.55   126.1  998.86   164.9  979.34
   232.8  946.76   261.9  934.09   281.3  927.22     291  924.39   310.4  919.84
   320.1  918.04   339.5  915.27   349.2  914.38   368.6  913.96     388   914.4
   426.8  916.98   446.8  917.34     456  918.77   485.1  931.87   504.5  939.26
   514.2  941.95   523.9  943.57   543.3  945.73   562.7  949.22   610.6  961.27
   658.3  975.28     687   984.6   725.2  997.98   763.4 1012.38   801.6 1027.43
#Mann= 3 , 0 , 0
       0     .06       0   426.8    .045       0   446.8      .1       0
Bank Sta=426.8,446.8
XS Rating Curve= 0 ,0
Exp/Cntr=0.3,0.1

Type RM Length L Ch R = 1 ,18777.4 ,523.8,508,499.9
XS GIS Cut Line= 2
     1593313.948      269689.569     1593873.844      269845.819
#Sta/Elev= 30
       0 1026.41    19.4  1016.5    38.8 1005.79    58.1  994.51    96.9  971.36
   116.3  960.21     126  954.89   145.3  944.93   164.7  936.18   174.4  932.31
   193.8  925.52   213.1  919.49   222.8  917.08   232.5  915.35   242.2  914.19
   251.9  913.64   271.3   913.5     287  913.69   290.6   913.8   300.3  914.88
     310  916.45   319.7  917.68   348.8  919.61   358.5  920.54   397.2  925.54
   503.8  938.22   513.5  939.89   523.2  942.29   542.5  948.24   581.3  960.95
#Mann= 3 , 0 , 0
       0     .06       0   271.3    .045       0     287     .06       0
Bank Sta=271.3,287
XS Rating Curve= 0 ,0
Exp/Cntr=0.3,0.1

Type RM Length L Ch R = 1 ,18269.3 ,197.5,236,231.9
XS GIS Cut Line= 2
     1593413.223      270146.468     1593895.501      270072.203
#Sta/Elev= 30
       0     960    19.5  953.55    29.3  949.85      39  945.46    48.8  940.43
    68.3  929.25    78.1   923.9    87.8  919.18    97.6  915.36   107.4  912.67
   117.1  911.39   126.9  911.03   165.9   911.7   195.2  912.02   204.9  911.93
   224.5  910.92   252.5  908.66   263.5  908.44   267.5  908.55   302.5  909.26
   312.3  909.69     322  910.85   331.8  912.79   341.6  915.29   361.1  921.38
   380.6  928.47   409.9  940.26   439.2  951.03   458.7  958.45     488     970
#Mann= 3 , 0 , 0
       0      .1       0   252.5    .045       0   267.5     .06       0
Bank Sta=252.5,267.5
XS Rating Curve= 0 ,0
Exp/Cntr=0.3,0.1

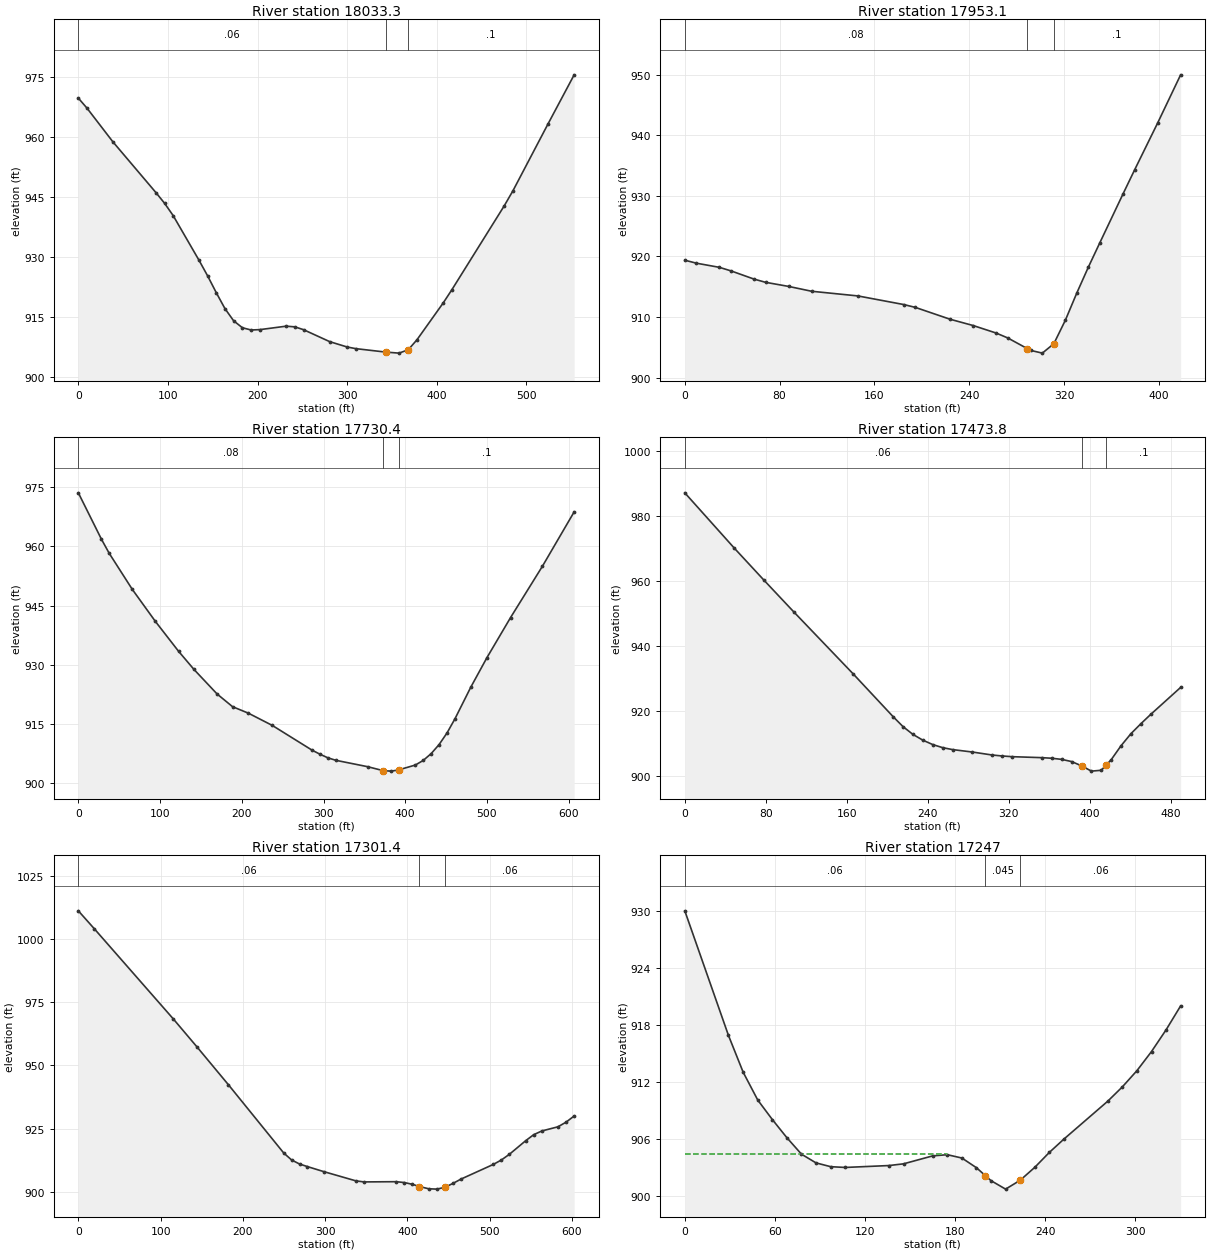
Type RM Length L Ch R = 1 ,18033.3 ,80.8,80.2,79.7
XS GIS Cut Line= 3
     1593379.052      270241.652     1593537.906      270280.715
     1593920.719      270207.798
#Sta/Elev= 30
       0  969.62     9.6  967.14    38.5  958.72    86.6  946.02    96.2  943.36
   105.8  940.28   134.7   929.1   144.3   925.2     154  920.98   163.6  917.04
   173.3  913.99   183.1  912.25   192.8  911.69   202.6  911.78   231.8  912.64
   241.5  912.48   251.3  911.77   280.5  908.78     300  907.44   309.7  907.03
   342.9  906.17   357.9  905.91   368.2  906.76   377.9  909.25   407.2  918.46
   416.9  921.77   475.3  942.72   485.1  946.52     524  963.12   553.3  975.44
#Mann= 3 , 0 , 0
       0     .06       0   342.9    .045       0   368.2      .1       0
Bank Sta=342.9,368.2
XS Rating Curve= 0 ,0
Exp/Cntr=0.3,0.1

Type RM Length L Ch R = 1 ,17953.1 ,230.6,222.7,214.8
XS GIS Cut Line= 2
     1593458.549      270371.667     1593869.628      270293.494
#Sta/Elev= 27
       0  919.38     9.7  918.89    29.2   918.2    38.9  917.62    58.4  916.26
    68.1  915.73    87.6  915.05     107  914.25     146  913.48   184.9  912.05
   194.6  911.58   223.8  909.63   243.3  908.59   262.7  907.35   272.5  906.54
     289  904.78   291.9  904.48   301.7  904.03   311.4  905.58   321.1  909.45
   330.9  914.01   340.6  918.26   350.3  922.29   369.8  930.33   379.5  934.27
     399  942.04   418.4     950
#Mann= 3 , 0 , 0
       0     .08       0     289    .045       0   311.4      .1       0
Bank Sta=289,311.4
XS Rating Curve= 0 ,0
Exp/Cntr=0.3,0.1

Type RM Length L Ch R = 1 ,17730.4 ,255.9,256.6,256.6
XS GIS Cut Line= 3
     1593558.739       270809.36     1593623.844      270632.277
     1593983.219      270418.735
#Sta/Elev= 30
       0  973.61    28.3  961.83    37.7  958.29      66  949.12    94.3  940.98
   122.6  933.42   141.5   928.8   169.8  922.57   188.7  919.35   208.1   917.7
   237.3   914.6   285.9  908.33   295.6   907.3   305.3  906.38     315  905.75
   353.9  904.13   373.4   903.1   383.1     903   391.8  903.31   412.3  904.54
     422  905.71   431.7  907.44   441.4  909.73   451.2  912.71   460.9   916.3
   480.3  924.33   499.8  931.73   528.9  941.97   567.8  954.96   606.7  968.78
#Mann= 3 , 0 , 0
       0     .08       0   373.4    .045       0   391.8      .1       0
Bank Sta=373.4,391.8
XS Rating Curve= 0 ,0
Exp/Cntr=0.3,0.1

Type RM Length L Ch R = 1 ,17473.8 ,166.2,172.3,178.3
XS GIS Cut Line= 2
     1593613.427      270905.715      1594040.51      270666.131
#Sta/Elev= 30
       0  987.15      49  970.12    78.4  960.24   107.7  950.55   166.5  931.45
   205.7  918.39   215.5  915.32   225.3  912.93     235  911.17   244.8  909.81
   254.6  908.86   264.4  908.26     284  907.51   303.6  906.59   313.4   906.3
   323.2  906.08   352.6  905.78   362.4   905.6   372.2  905.25     382  904.58
   391.8  903.28   401.6  901.64   411.3   901.9   415.9  903.42   421.1  905.14
   430.9  909.46   440.7  913.17   450.5  916.22   460.3  919.11   489.7  927.36
#Mann= 3 , 0 , 0
       0     .06       0   391.8    .045       0   415.9      .1       0
Bank Sta=391.8,415.9
XS Rating Curve= 0 ,0
Exp/Cntr=0.3,0.1

Type RM Length L Ch R = 1 ,17301.4 ,61.8,54.4,47
XS GIS Cut Line= 3
     1593661.821      271058.167     1593889.182      270897.536
     1594198.065      270799.112
#Sta/Elev= 30
       0 1011.11    19.2  1004.1   115.2  968.46     144  957.39   182.4  942.36
   249.6  915.38   259.2  912.62   268.8  911.03   278.4     910     298  908.04
   337.3  904.36   347.2  903.94   386.4  904.03   396.3  903.68   406.1  902.99
   414.5  902.12   425.7  901.24   435.6  901.09   445.4   901.8   455.2  903.33
     465  905.05   504.3  910.85   514.2  912.62     524  914.89   543.6  920.21
   553.4  922.61   563.3  924.08   582.9  925.73   592.7  927.55   602.6     930
#Mann= 3 , 0 , 0
       0     .06       0   414.5    .045       0   445.4     .06       0
Bank Sta=414.5,445.4
XS Rating Curve= 0 ,0
Exp/Cntr=0.3,0.1

Type RM Length L Ch R = 1 ,17247   ,102.5,82.5,82.5
XS GIS Cut Line= 2
     1593878.965      271022.338     1594148.546      270831.496
#Sta/Elev= 29
       0     930    29.1  916.89    38.9  913.02    48.6   910.1    58.3  908.05
      68  906.14    77.7  904.41    87.4  903.49    97.2  903.09   106.9  903.01
     136  903.21   145.7  903.39   165.2  904.23   174.9  904.35   184.6     904
   194.3  902.98   200.2  902.15     204  901.62   213.7  900.73   223.4  901.66
   233.2  903.03   242.9   904.6   252.6     906   281.7  909.97   291.4  911.47
   301.2  913.19   310.9   915.2   320.6  917.48   330.3     920
#Mann= 3 , 0 , 0
       0     .06       0   200.2    .045       0   223.4     .06       0
#XS Ineff= 2 , 0
          174.51  904.42
Permanent Ineff=
       F       F
Bank Sta=200.2,223.4
XS Rating Curve= 0 ,0
Exp/Cntr=0.3,0.1

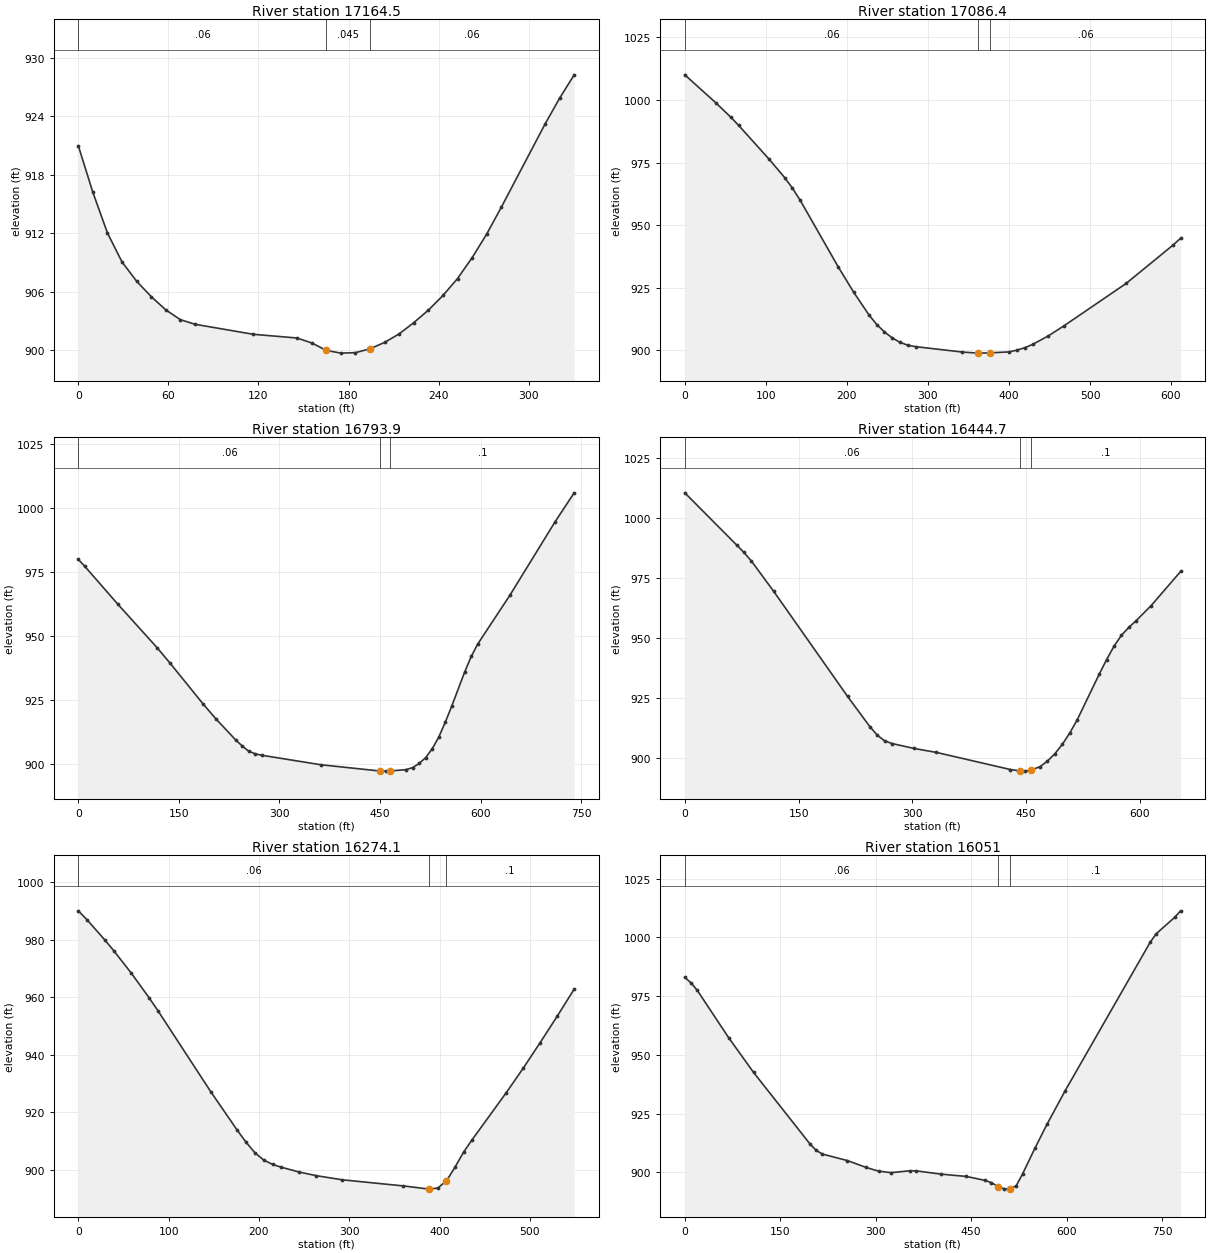
Type RM Length L Ch R = 1 ,17164.5 ,50,78.1,85.4
XS GIS Cut Line= 2
     1593927.707      271081.859     1594197.288      270891.017
#Sta/Elev= 28
       0  920.98     9.7   916.2    19.4  912.04    29.1  909.07    38.9  907.08
    48.6  905.51    58.3  904.15      68  903.15    77.7  902.68   116.6  901.65
   145.7  901.27   155.4  900.77   165.2     900   174.9  899.72   184.6  899.77
   194.3  900.16     204  900.82   213.7  901.69   223.4  902.84   233.2  904.13
   242.9  905.63   252.6  907.37   262.3   909.5     272  911.92   281.7  914.66
   310.9  923.21   320.6  925.86   330.3  928.26
#Mann= 3 , 0 , 0
       0     .06       0   165.2    .045       0   194.3     .06       0
Bank Sta=165.2,194.3
XS Rating Curve= 0 ,0
Exp/Cntr=0.3,0.1

Type RM Length L Ch R = 1 ,17086.4 ,304.9,292.5,274.3
XS GIS Cut Line= 3
     1593745.813      271192.808     1593979.317      271088.043
     1594293.739      270921.257
#Sta/Elev= 30
       0    1010    37.9  998.95    56.9  993.04    66.4  989.84   104.3  976.22
   123.2     969   132.7  964.81   142.2  960.02   189.6  933.18   208.5  923.16
   227.5  914.04     237  910.29   246.4  907.35   255.9  905.02   265.6   903.2
   275.2  902.07   284.8  901.49   342.5  899.34   361.7  898.91   362.1  898.91
   377.1  899.03   400.2   899.4   409.8   900.1   419.5  901.08   429.1  902.37
   448.3  905.75   467.6  909.75   544.5  926.71   602.2  941.98   611.8  944.78
#Mann= 3 , 0 , 0
       0     .06       0   362.1    .045       0   377.1     .06       0
Bank Sta=362.1,377.1
XS Rating Curve= 0 ,0
Exp/Cntr=0.3,0.1

Type RM Length L Ch R = 1 ,16793.9 ,354,349.2,349.7
XS GIS Cut Line= 4
     1594222.802      271572.381     1594212.385      271338.006
     1594355.614      271048.944     1594485.823       270921.34
#Sta/Elev= 30
       0  979.79     9.8  977.07    58.6  962.42   117.3  945.41   136.8  939.33
   185.7  923.51   205.3  917.54   234.6  909.38   244.4     907   254.2  904.93
   263.9  903.92   273.7  903.36   361.7  899.66   450.4   897.2   459.4  897.17
   465.4  897.24   488.8  897.76   498.6  898.54   508.3  900.16   518.1  902.46
   527.9  905.93   537.7  910.54   547.4  916.32   557.2  922.74   576.4     936
     586  941.92   595.6  946.76   643.6   965.8   710.7  994.36   739.5 1005.81
#Mann= 3 , 0 , 0
       0     .06       0   450.4    .045       0   465.4      .1       0
Bank Sta=450.4,465.4
XS Rating Curve= 0 ,0
Exp/Cntr=0.3,0.1

Type RM Length L Ch R = 1 ,16444.7 ,177.5,170.6,166.6
XS GIS Cut Line= 2
     1594371.239       271733.84     1594681.135      271158.319
#Sta/Elev= 30
       0 1010.57    68.3  988.82      78  985.67    87.8   982.1   117.1  969.49
   214.6  925.58   243.9  913.01   253.7  909.42   263.4  907.04   273.2  905.93
   302.4  903.86   331.7  902.22   429.3  895.07   441.5  894.55   448.8  894.41
   456.5  894.85   468.3  896.28     478  898.57   487.8  901.66   497.6  905.56
   507.3  910.22   517.1  915.72   546.3  934.87   556.1     941   565.8  946.56
   575.6  951.12   585.4  954.43   595.1  957.24   614.6  963.45   653.6  977.74
#Mann= 3 , 0 , 0
       0     .06       0   441.5    .045       0   456.5      .1       0
Bank Sta=441.5,456.5
XS Rating Curve= 0 ,0
Exp/Cntr=0.3,0.1

Type RM Length L Ch R = 1 ,16274.1 ,229.2,223.1,213.8
XS GIS Cut Line= 4
     1594597.199      271783.352     1594704.009      271574.493
     1594738.557      271404.695     1594792.811      271274.486
#Sta/Elev= 30
       0     990     9.8  986.84    29.3  979.88    39.1  976.18    58.6  968.35
    78.2  959.82      88  955.32   146.6  927.09   175.9   913.7   185.7  909.51
   195.5  905.85   205.3   903.3     215   901.8   224.8  900.81   244.2  899.17
   263.5  897.87   292.3  896.44   359.7  894.32   388.6   893.2   398.2  893.61
   406.9  895.97   407.9  896.24   417.3     901   426.7  906.17   436.1  910.45
   473.7  926.73   492.5  935.26   511.3  944.18   530.1  953.33   548.9  962.75
#Mann= 3 , 0 , 0
       0     .06       0   388.6    .045       0   406.9      .1       0
Bank Sta=388.6,406.9
XS Rating Curve= 0 ,0
Exp/Cntr=0.3,0.1

Type RM Length L Ch R = 1 ,16051   ,240.1,247.3,254.5
XS GIS Cut Line= 3
     1594985.823      271939.569     1594944.156      271400.506
     1594899.885      271166.131
#Sta/Elev= 30
       0  983.01     9.8  980.67    19.7  977.46    68.8   957.4   108.1  942.56
   196.6  912.18   206.4  909.43   216.3  907.82   255.6  905.06   285.1  902.12
   304.7  900.55   324.4  899.92   353.9  900.73   363.7  900.68     403  899.28
   442.4  898.31   471.9  896.62   481.7  895.68   492.4  894.02   501.4   893.1
   511.2  892.91     521  894.43   530.8  899.36   550.2   910.3   569.3  920.54
   597.9  934.85   731.5  998.02     741 1001.62   769.6  1008.5   779.2 1011.33
#Mann= 3 , 0 , 0
       0     .06       0   492.4    .045       0   511.2      .1       0
Bank Sta=492.4,511.2
XS Rating Curve= 0 ,0
Exp/Cntr=0.3,0.1

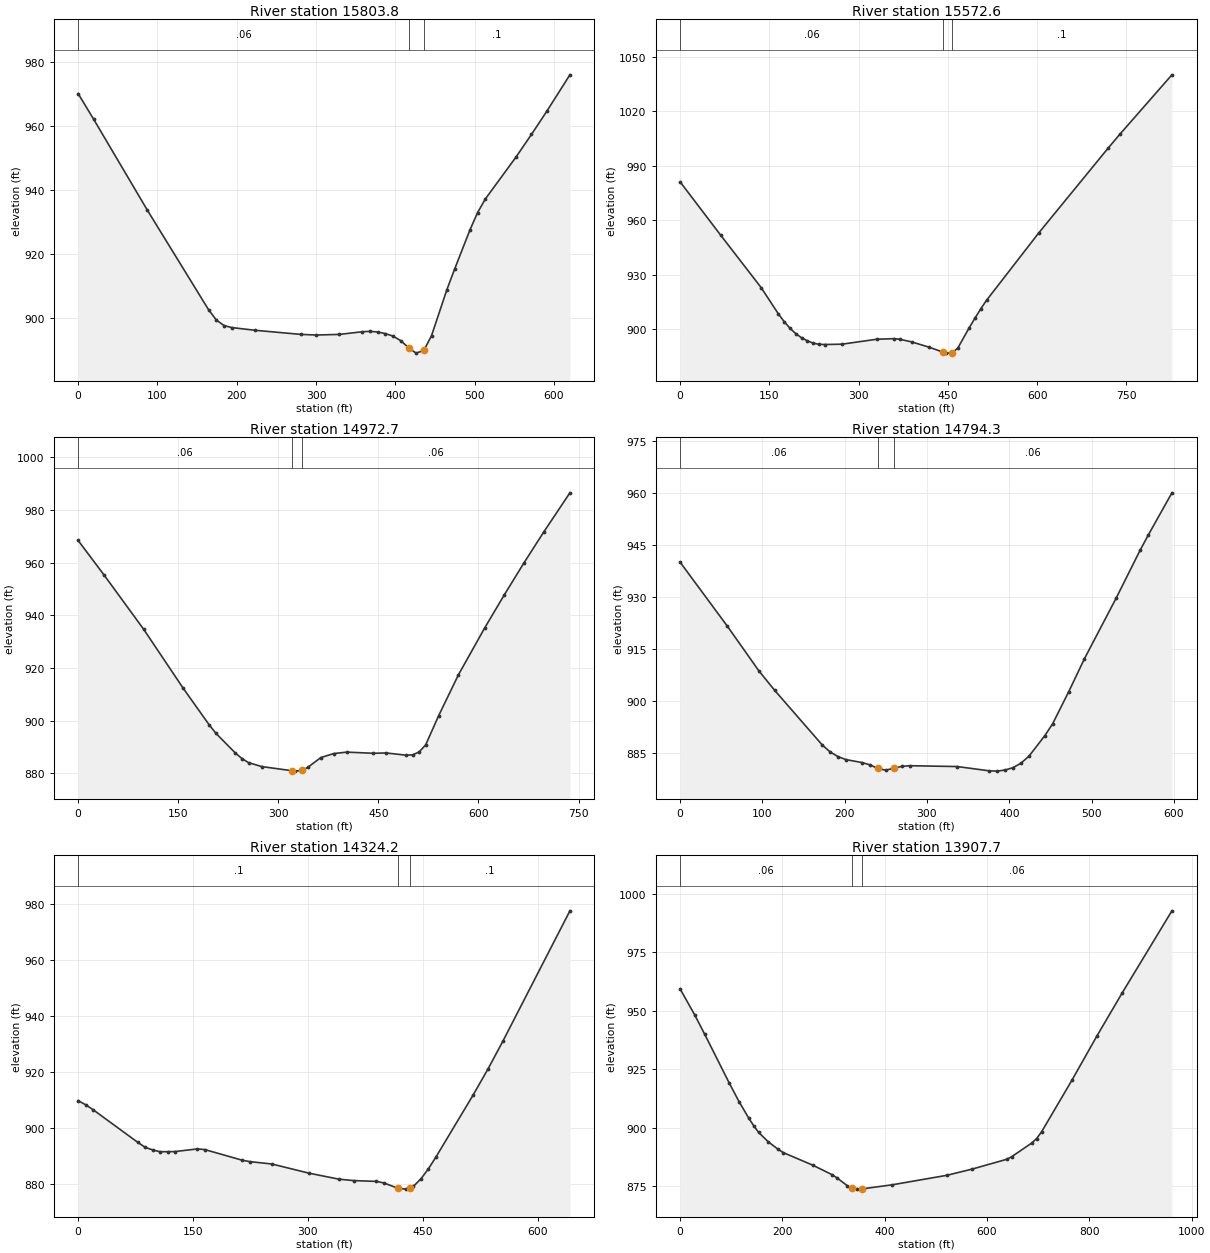
Type RM Length L Ch R = 1 ,15803.8 ,229.6,231.2,232.5
XS GIS Cut Line= 3
     1595103.965       271899.31     1595130.778      271717.308
     1595235.596      271293.884
#Sta/Elev= 30
       0     970    19.4  962.09    87.1  933.78   164.6  902.66   174.3   899.5
     184  897.77   193.7  897.14   222.7  896.31   280.9  895.01   300.3  894.82
   329.4  895.01   358.4  895.84   368.1  895.97   377.8  895.76   387.5  895.27
   397.2  894.48   406.9  893.05   417.8  890.65   426.3  889.18     436  890.02
   445.7  894.63   465.1  908.97   474.8  915.35   494.2  927.58   503.8  932.96
   513.5  937.17   552.3  950.27   571.7  957.29   591.1  964.52   620.2  975.85
#Mann= 3 , 0 , 0
       0     .06       0   417.8    .045       0     436      .1       0
Bank Sta=417.8,436
XS Rating Curve= 0 ,0
Exp/Cntr=0.3,0.1

Type RM Length L Ch R = 1 ,15572.6 ,592.5,599.9,607.3
XS GIS Cut Line= 3
     1595272.281       271983.84     1595418.114      271520.298
     1595454.573      271181.756
#Sta/Elev= 30
       0  981.24      68  951.94   136.1  923.04   165.2  908.51   174.9  904.25
   184.7  900.61   194.4  897.66   204.1   895.4   213.8  893.72   223.5  892.46
   233.2  891.81     243   891.7   272.1  891.88   330.4   894.6   359.6  894.92
   369.3  894.56   388.8  893.16   417.9  890.26   441.2  887.57   447.1  887.02
   456.2  886.95   466.5  889.68   485.9     901   495.7  906.34   505.4  911.46
   515.1  916.14   602.7  953.17   719.4   999.9   738.9 1007.45   826.4 1040.18
#Mann= 3 , 0 , 0
       0     .06       0   441.2    .045       0   456.2      .1       0
Bank Sta=441.2,456.2
XS Rating Curve= 0 ,0
Exp/Cntr=0.3,0.1

Type RM Length L Ch R = 1 ,14972.7 ,178.3,178.3,178.1
XS GIS Cut Line= 2
     1595612.559      272201.287     1596052.663      271610.142
#Sta/Elev= 30
       0  968.47    39.3   955.2    98.3   934.7   157.2  912.43   196.5   898.4
   206.4  895.25   235.8  887.68   245.7  885.59   255.5  884.07   275.1  882.58
   320.1  881.02   324.3  880.85   335.1   881.1   343.9  882.23   363.6  885.99
   383.2  887.53   402.9  888.07   442.2  887.63   461.8  887.75   491.3  886.91
   501.2  887.02     511  888.12   520.8  890.81   540.4  901.97   569.9  917.42
   609.2   935.2   638.7  947.81   668.2  959.97   697.7  971.65     737  986.56
#Mann= 3 , 0 , 0
       0     .06       0   320.1    .045       0   335.1     .06       0
Bank Sta=320.1,335.1
XS Rating Curve= 0 ,0
Exp/Cntr=0.3,0.1

Type RM Length L Ch R = 1 ,14794.3 ,468.2,470.1,471.4
XS GIS Cut Line= 3
     1595755.714      272244.814     1595878.457      272137.678
     1596135.729       271787.19
#Sta/Elev= 30
       0     940    57.5  921.52    95.8  908.65     115  903.04   172.6  887.35
   182.2  885.33   191.9  883.96   201.6   883.1   220.9  882.26   230.6   881.6
   240.2  880.57   249.9  880.05   259.5  880.61   269.2  881.15   278.9  881.34
   336.8   881.1   375.5  879.87   385.1  879.78   394.8  880.09   404.5  880.77
   414.1  882.05   423.8  884.04   443.1  889.96   452.8  893.46   472.1   902.6
   491.4  912.19   530.1  929.73     559  943.43   568.7  947.72   597.7     960
#Mann= 3 , 0 , 0
       0     .06       0   240.2    .045       0   259.5     .06       0
Bank Sta=240.2,259.5
XS Rating Curve= 0 ,0
Exp/Cntr=0.3,0.1

Type RM Length L Ch R = 1 ,14324.2 ,397.4,416.6,435.7
XS GIS Cut Line= 2
       1596056.1      272483.358     1596438.912      271967.733
#Sta/Elev= 30
       0  909.64     9.7  908.19    19.5  906.41    77.8  894.74    87.6  892.94
    97.3  892.01     107  891.37   116.8  891.38   126.5  891.43   155.7  892.37
   165.4  892.14   214.1  888.35   223.8  887.84     253  886.98   301.6  883.69
   340.6  881.55     360  881.04   389.2  880.76   398.9  880.24   418.2  878.25
   428.1  877.99   433.2  878.52   437.9     879   447.6  881.66   457.3   885.2
     467  889.36   515.7   911.6   535.2  920.95   554.6  930.88   642.2  977.54
#Mann= 3 , 0 , 0
       0      .1       0   418.2    .045       0   433.2      .1       0
Bank Sta=418.2,433.2
XS Rating Curve= 0 ,0
Exp/Cntr=0.3,0.1

Type RM Length L Ch R = 1 ,13907.7 ,267.6,261.8,255.9
XS GIS Cut Line= 4
      1596169.85      272708.557     1596360.823      272480.693
     1596729.746      272448.141     1597022.715      272469.842
#Sta/Elev= 30
       0  959.42    28.8  948.18      48  940.05    95.9  919.23   115.1  911.27
   134.3  904.11   143.9  900.91   153.4  898.09   172.6  893.99   191.8  890.83
   201.4  889.47     259   884.1   297.3  879.98   307.1  878.57   326.6  875.32
   336.3  874.16     346  873.83   355.8  873.94   414.3  875.67   521.5  879.74
   570.2  882.36   638.4  886.58   648.2   887.7   687.2  893.51     697  895.47
   706.8   898.4   765.6  920.28   814.6  939.24   863.5  957.47   961.4  992.81
#Mann= 3 , 0 , 0
       0     .06       0   336.3    .045       0   355.8     .06       0
Bank Sta=336.3,355.8
XS Rating Curve= 0 ,0
Exp/Cntr=0.3,0.1

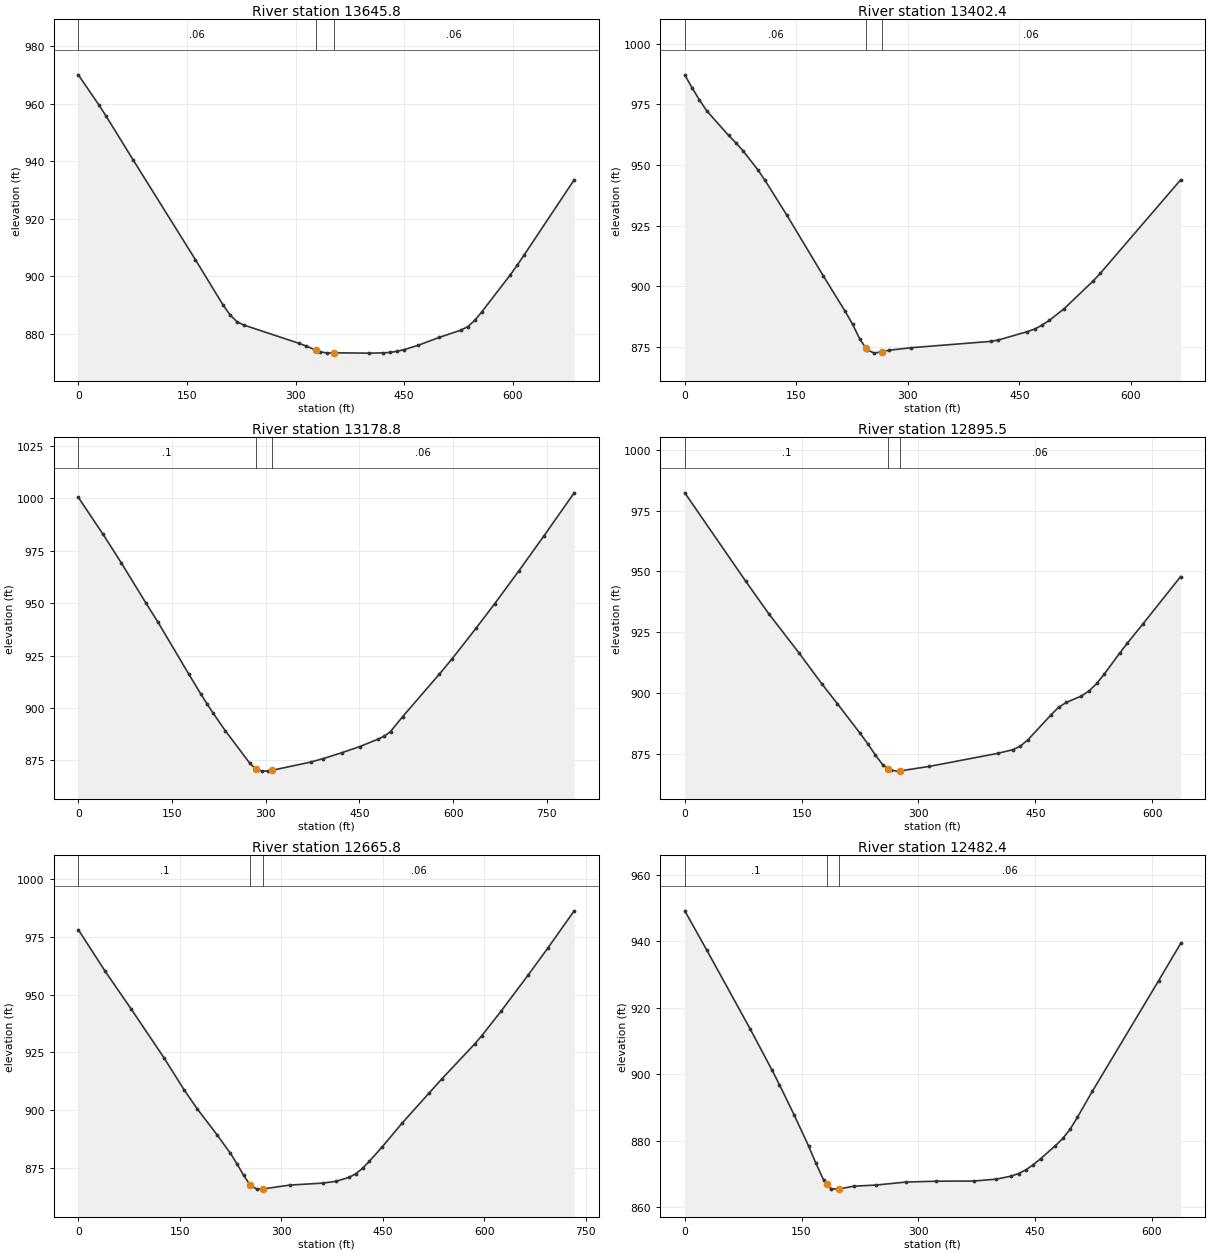
Type RM Length L Ch R = 1 ,13645.8 ,251.7,243.5,235.1
XS GIS Cut Line= 4
     1596292.285       272880.62     1596494.199      272706.778
     1596719.894      272619.972     1596893.505       272587.42
#Sta/Elev= 30
       0     970    28.6  959.48    38.1  955.78    76.1  940.32   161.8  905.81
   199.8  890.16   209.4  886.74   218.9  884.34   228.4  883.16   305.1  876.78
   314.8  875.86   328.6  874.37   334.2  873.83   343.6  873.45   353.5  873.51
   401.9   873.4   421.2  873.49   430.9  873.66   440.6  874.06   450.2  874.63
   469.6  876.14   498.6  878.87   527.9  881.34   537.7  882.55   547.5  884.75
   557.3  887.72   596.6  900.53   606.4  903.98   616.2  907.62   684.9  933.54
#Mann= 3 , 0 , 0
       0     .06       0   328.6    .045       0   353.5     .06       0
Bank Sta=328.6,353.5
XS Rating Curve= 0 ,0
Exp/Cntr=0.3,0.1

Type RM Length L Ch R = 1 ,13402.4 ,224.6,223.6,222.2
XS GIS Cut Line= 2
     1596431.135      273061.965     1596938.948      272629.673
#Sta/Elev= 30
       0  987.21     9.8  981.84    19.6   976.9    29.4  972.43    58.8  962.26
    68.6  959.24    78.5  955.84    98.1  948.12   107.9  943.72   137.3  929.35
   186.3  904.34   215.8  889.67   225.6  884.45   235.4   878.3     244  874.41
   245.2  873.87     255   872.5   264.8  873.08   274.6  873.69     304  874.72
   411.9  877.35   421.7  877.91   460.9  881.38   470.8  882.43   480.6  884.06
   490.4  886.03     510  890.76   549.2  902.22     559  905.45   666.9  943.93
#Mann= 3 , 0 , 0
       0     .06       0     244    .045       0   264.8     .06       0
Bank Sta=244,264.8
XS Rating Curve= 0 ,0
Exp/Cntr=0.3,0.1

Type RM Length L Ch R = 1 ,13178.8 ,282.1,283.3,284
XS GIS Cut Line= 2
     1596579.573      273231.235     1597149.885      272679.152
#Sta/Elev= 30
       0 1000.41    39.2  982.97    68.6  969.28   107.8  950.23   127.4  940.99
   176.4  916.38     196  906.74   205.8  902.12   215.6  897.66   235.2  889.25
   274.4  873.73   284.2  870.86     294  869.93   303.8  870.02     310  870.32
   372.4  874.27     392   875.9   421.4  878.67   450.8  881.66   480.2  885.21
     490  886.63   499.8  888.81   519.4  895.96   578.2  916.25   597.8  923.25
     637  938.13   666.4  949.66   705.6  965.52   744.8  981.78   793.8 1002.56
#Mann= 3 , 0 , 0
       0      .1       0   284.2    .045       0     310     .06       0
Bank Sta=284.2,310
XS Rating Curve= 0 ,0
Exp/Cntr=0.3,0.1

Type RM Length L Ch R = 1 ,12895.5 ,227.2,229.7,232.2
XS GIS Cut Line= 2
     1596773.149      273392.151      1597250.58      272971.144
#Sta/Elev= 30
       0  982.31    78.3  945.92   107.7  932.62   146.9  916.35   176.3  903.59
   195.9  895.58   225.2  883.33     235  879.07   244.8  874.42   254.6  870.24
     261   868.9   264.4  868.19   274.2  867.85     276  867.92   313.4  869.77
   401.5  875.15   421.1  876.66   430.9  878.17   440.7  880.82   470.1  890.98
   479.9  894.11   489.6  896.09   509.2  898.76     519  900.87   528.8   903.9
   538.6  907.82   558.2  916.36     568  920.46   587.6  928.18   636.5  947.87
#Mann= 3 , 0 , 0
       0      .1       0     261    .045       0     276     .06       0
Bank Sta=261,276
XS Rating Curve= 0 ,0
Exp/Cntr=0.3,0.1

Type RM Length L Ch R = 1 ,12665.8 ,172.5,183.4,195.4
XS GIS Cut Line= 2
     1596897.281      273548.944     1597496.239      273127.069
#Sta/Elev= 30
       0   978.2    39.1   960.4    78.2  943.74     127  922.44   156.3  908.73
   175.8  900.45   205.1  889.19   224.7  881.19   234.4  876.67   244.2  871.66
     254   867.4   263.7  865.66   273.5  865.79   312.6  867.42   361.4  868.28
     381  869.06   400.5  870.84   410.3   872.4     420  874.72   429.8   877.7
   449.3  884.11   478.6  894.36   517.7  907.17   537.2  913.51   586.1  928.78
   595.9  932.14   625.2  943.08   664.2  958.36   693.6  970.18   732.6  986.38
#Mann= 3 , 0 , 0
       0      .1       0     254    .045       0   273.5     .06       0
Bank Sta=254,273.5
XS Rating Curve= 0 ,0
Exp/Cntr=0.3,0.1

Type RM Length L Ch R = 1 ,12482.4 ,310.8,310.7,309.6
XS GIS Cut Line= 4
     1596987.993      273598.314     1597145.241      273574.833
     1597412.168      273535.771       1597576.1      273407.342
#Sta/Elev= 30
       0  949.09    28.1  937.34    84.2  913.49   112.2  901.16   121.6  896.83
   140.3  887.83     159  878.41   168.6  873.14   178.3  868.19   182.5  867.03
   187.9  865.54   197.5  865.43   216.8  866.31   245.7  866.66   284.2  867.56
   322.8  867.81     371  867.87   399.9  868.42   419.1  869.33   428.8  870.12
   438.2  871.23   447.7  872.79   457.2  874.59   476.1  878.49   485.6  880.65
     495  883.44   504.5  887.06   523.4  894.78   608.6  928.04     637  939.27
#Mann= 3 , 0 , 0
       0      .1       0   182.5    .045       0   197.5     .06       0
Bank Sta=182.5,197.5
XS Rating Curve= 0 ,0
Exp/Cntr=0.3,0.1

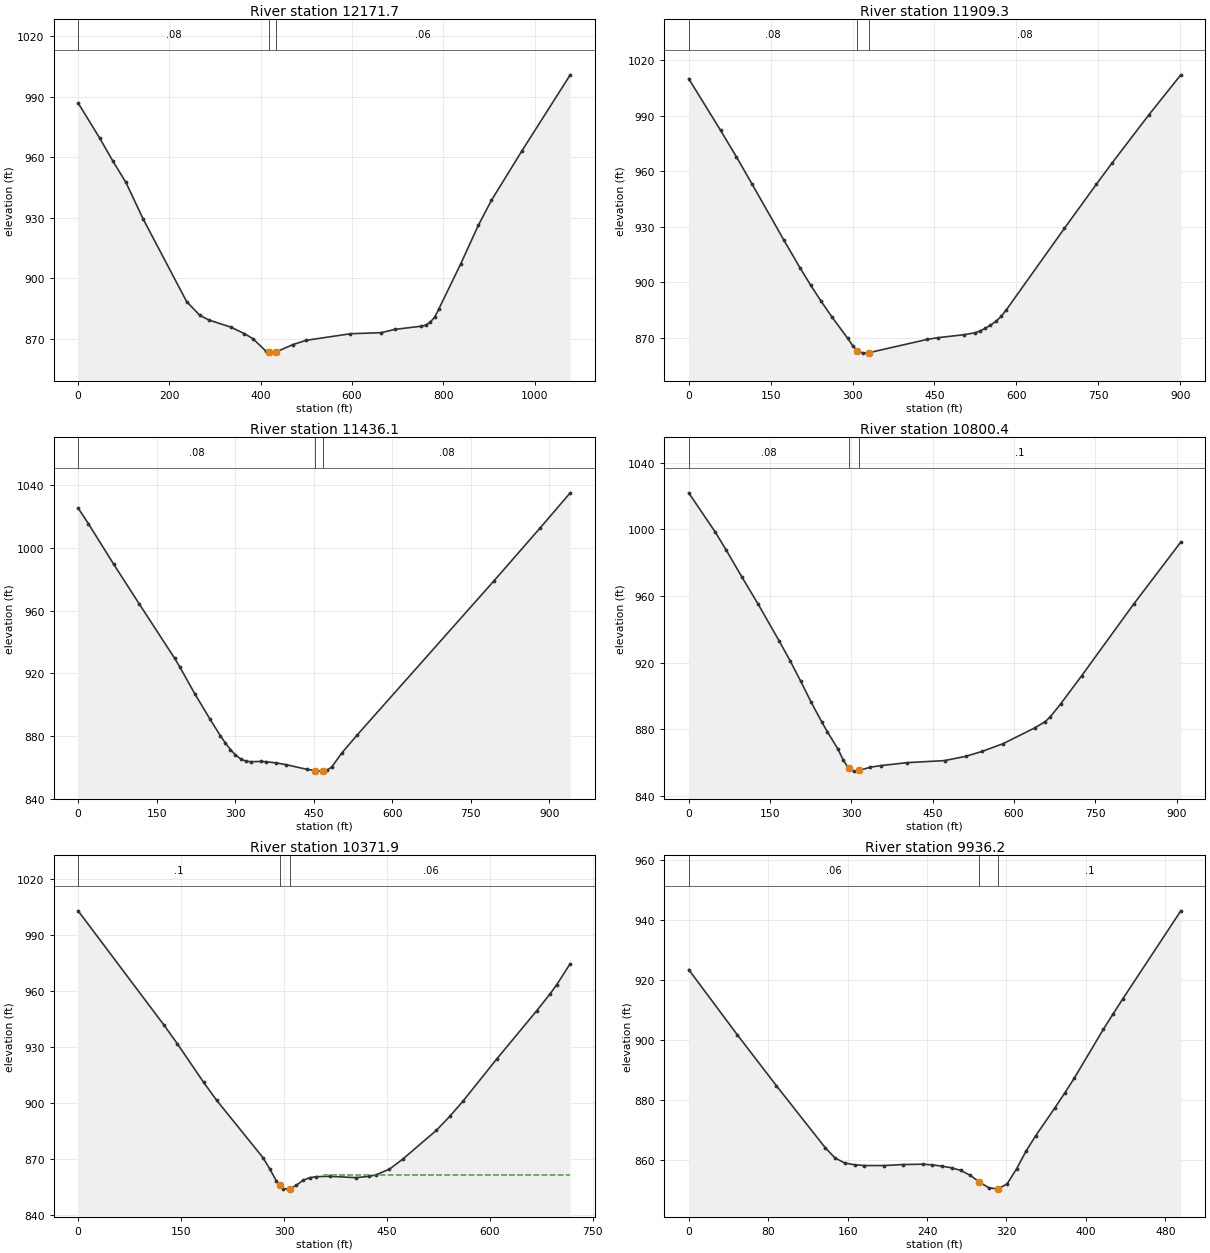
Type RM Length L Ch R = 1 ,12171.7 ,268.6,262.4,255.7
XS GIS Cut Line= 4
     1597048.757      274119.148     1597087.819      273884.773
     1597621.673      273784.946     1597869.069      273949.877
#Sta/Elev= 30
       0  986.81    47.5  969.28      76  958.03   104.6  947.44   142.6  929.21
   237.6  888.36   266.7  881.49   286.1  879.22   334.6  875.66   363.7   872.5
   383.1  869.92   412.2  863.59   417.4  863.16   421.9  862.78   432.4  863.22
   470.4  867.02   499.5  869.13   596.4  872.39   664.3  872.94   693.4  874.53
   751.6  876.13   761.3  876.64     771  878.06   780.7  880.49   790.3  884.76
   838.3  907.14   876.6  926.13   905.4  938.56   972.5   963.2    1078 1000.77
#Mann= 3 , 0 , 0
       0     .08       0   417.4    .045       0   432.4     .06       0
Bank Sta=417.4,432.4
XS Rating Curve= 0 ,0
Exp/Cntr=0.3,0.1

Type RM Length L Ch R = 1 ,11909.3 ,460.6,473.2,481.6
XS GIS Cut Line= 3
     1597056.135      274236.444     1597454.573       274015.09
     1597899.885      274017.694
#Sta/Elev= 30
       0 1009.98    58.2  982.13    87.3  967.77   116.4  952.84   174.6  922.55
   203.6  907.86     223  898.51   242.4  889.69   261.8  881.38   290.9  869.72
   300.6   865.5   308.9  862.94   310.3  862.51     320  861.63   329.7  861.85
   436.4  869.03   455.8  869.96   504.2   871.6   523.6  872.57   533.2  873.56
   542.9  875.03   552.6  876.76   562.3  878.75     572  881.45   581.6  885.04
   688.1  929.16   746.2  952.83   775.3  964.46     843  990.61   901.1 1012.09
#Mann= 3 , 0 , 0
       0     .08       0   308.9    .045       0   329.7     .08       0
Bank Sta=308.9,329.7
XS Rating Curve= 0 ,0
Exp/Cntr=0.3,0.1

Type RM Length L Ch R = 1 ,11436.1 ,625.7,635.7,649.1
XS GIS Cut Line= 3
     1597110.823      274533.319     1597605.614      274436.965
     1598022.281       274309.36
#Sta/Elev= 30
       0 1025.52    19.4 1015.63    67.9  989.65   116.3  964.51   184.2  929.64
   193.9  924.21     223  906.84     252  890.66   271.4  880.28   281.1  875.53
   290.8  871.35   300.5  867.91   310.2  865.39   319.9  863.96   329.6  863.56
     349  863.75   358.7  863.58   378.1  862.82   397.4  861.68   436.2  858.76
     453  857.84   465.3  857.56     468  857.67     475  857.97   484.7   860.4
   504.1  869.37   533.1  880.73   794.6  979.21   881.8 1012.62   939.8 1035.23
#Mann= 3 , 0 , 0
       0     .08       0     453    .045       0     468     .08       0
Bank Sta=453,468
XS Rating Curve= 0 ,0
Exp/Cntr=0.3,0.1

Type RM Length L Ch R = 1 ,10800.4 ,424.1,428.5,432.4
XS GIS Cut Line= 3
     1597014.469      274783.319     1597537.906      275033.319
     1597733.219       275296.34
#Sta/Elev= 30
       0 1021.88    49.2  998.22    68.8  987.72    98.3  971.25   127.8  955.23
   167.1  932.83   186.8  921.23   206.5  908.86   226.1  896.07   245.8  884.13
   255.6  878.56   275.3  868.07   285.1  861.52     295  856.47   304.8  854.85
   314.6  855.28   334.3  857.16   353.9  858.15   403.1  859.94   471.9  861.18
   511.2  863.75   540.8  866.65   580.1  871.35   637.9  880.76   657.2  884.48
   666.8  887.39   686.1   895.2   724.6     912     821  955.21   907.7  992.35
#Mann= 3 , 0 , 0
       0     .08       0     295    .045       0   314.6      .1       0
Bank Sta=295,314.6
XS Rating Curve= 0 ,0
Exp/Cntr=0.3,0.1

Type RM Length L Ch R = 1 ,10371.9 ,435.7,435.7,435.2
XS GIS Cut Line= 4
     1596787.906       275059.36     1597011.864      275241.652
     1597162.602      275347.837     1597338.383      275517.108
#Sta/Elev= 30
       0 1003.07   125.1  941.78   144.4  931.86   182.9  911.04   202.1  901.31
   269.5  870.59   279.1  864.73   288.8  858.16   294.4  855.76   298.5     854
   308.2  853.75   309.4     854   317.9  855.79   327.6  858.46   337.3  859.86
     347  860.44   366.4  860.62   405.2  859.91   424.6  860.64   434.3  861.44
   453.7  864.48   473.2  869.88     522  885.25   541.5  892.75     561     901
   609.8  923.46   668.4   949.5   687.9  958.55   697.7  963.54   717.2  974.74
#Mann= 3 , 0 , 0
       0      .1       0   294.4    .045       0   309.4     .06       0
#XS Ineff= 2 , 0
                          358.31          861.32
Permanent Ineff=
       F       F
Bank Sta=294.4,309.4
XS Rating Curve= 0 ,0
Exp/Cntr=0.3,0.1

Type RM Length L Ch R = 1 ,9936.2  ,217.8,224.7,231.5
XS GIS Cut Line= 4
     1596639.251      275378.913      1596810.28       275568.54
     1596881.461      275613.679     1596994.308      275721.318
#Sta/Elev= 30
       0  923.37    49.1  901.61    88.4  884.69   137.5   864.1   147.3  860.69
   157.2     859     167  858.42   176.8  858.16   196.4  858.15   216.1   858.5
   235.7   858.6   245.5  858.38   255.4  857.93   264.7  857.41   274.1  856.52
   283.5  854.91   292.8  852.64   302.2  850.78   311.6  850.31   320.9  852.17
   330.3  857.12   339.6  862.87   349.4  868.06   368.9  877.42   378.6  882.24
   388.4   887.3   417.6  903.51   427.4  908.62   437.1   913.6   495.6  942.93
#Mann= 3 , 0 , 0
       0     .06       0   292.8    .045       0   311.6      .1       0
Bank Sta=292.8,311.6
XS Rating Curve= 0 ,0
Exp/Cntr=0.3,0.1