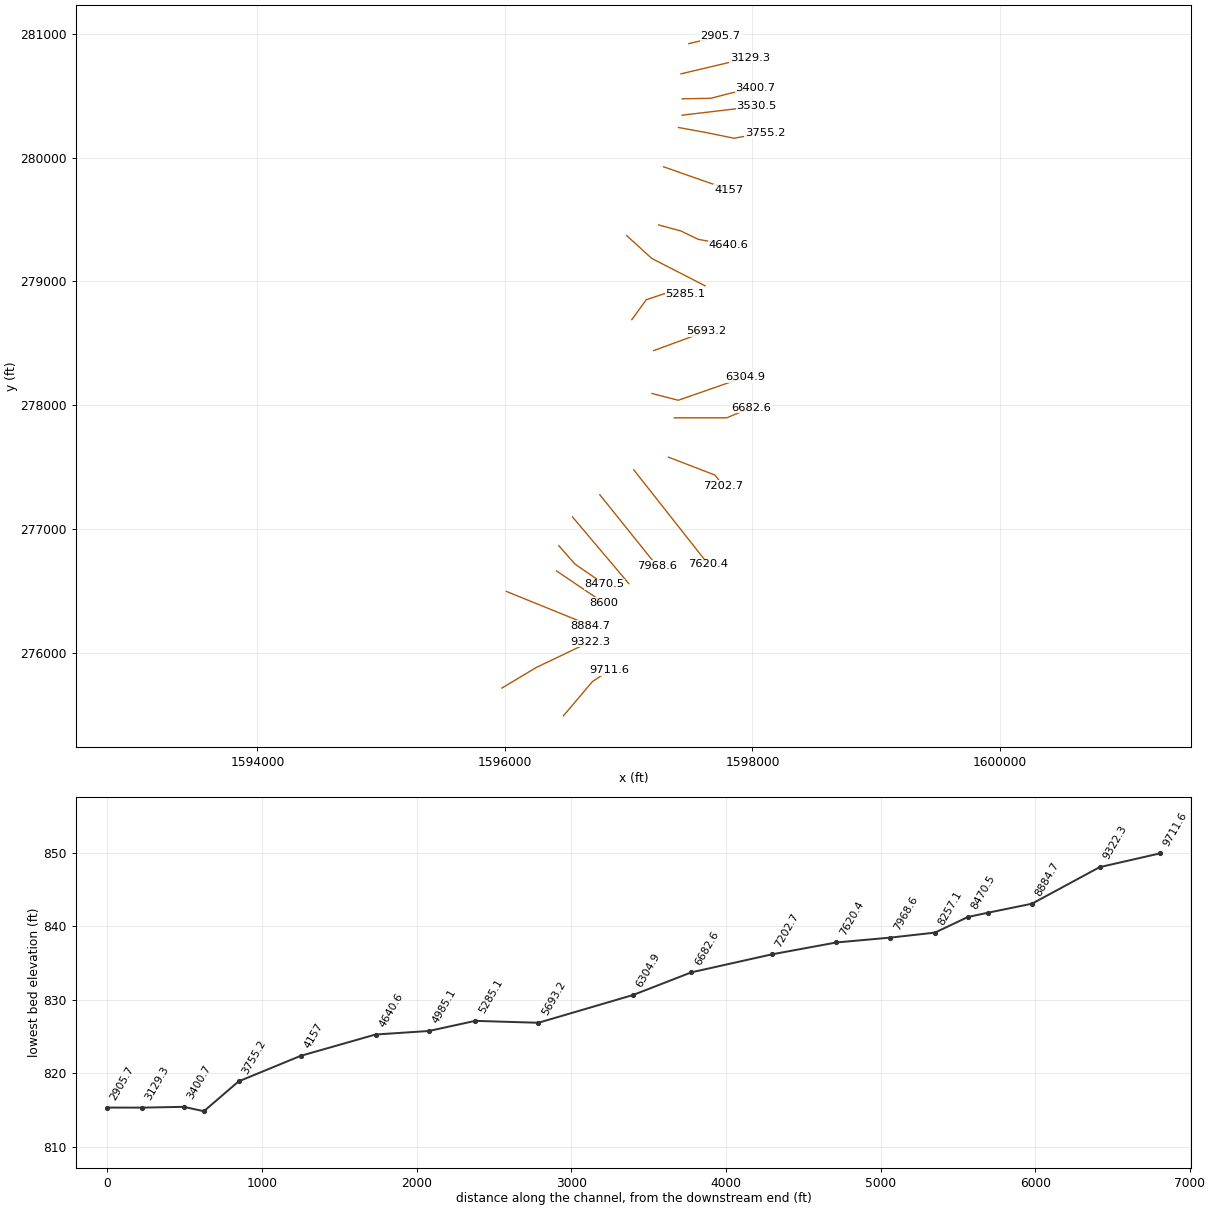
HEC-RAS study RFKRNLDCK.prj: RFKRNLDCK

--- RFKRNLDCK.g01 (geometry) --- (continued)

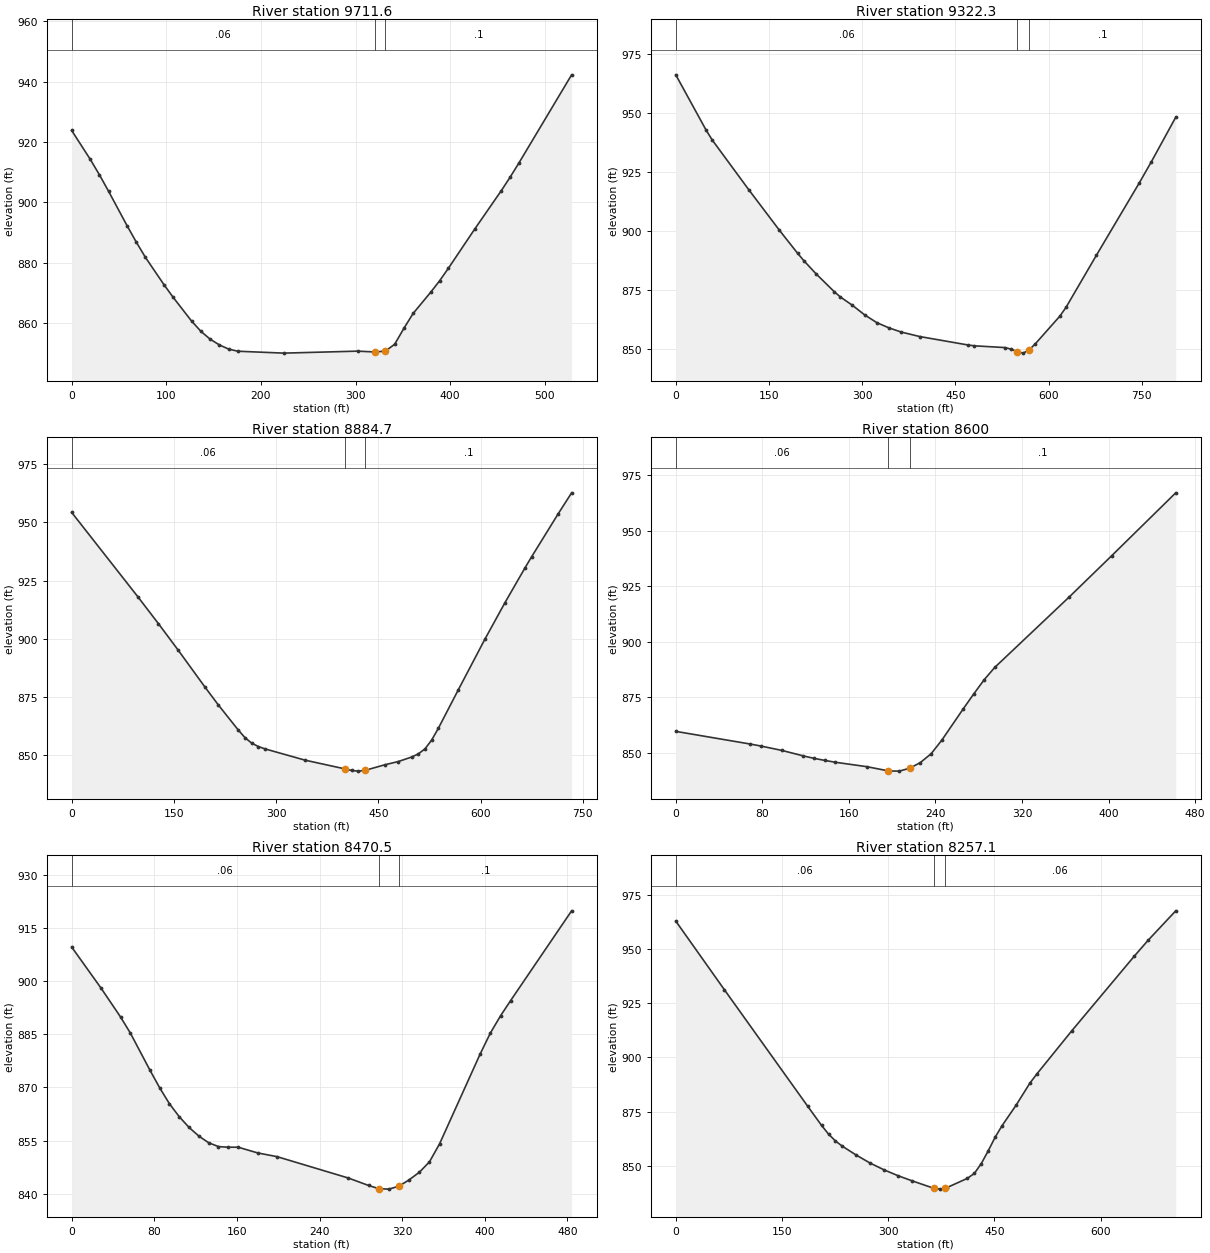
Type RM Length L Ch R = 1 ,9711.6  ,399.6,389.2,377.9
XS GIS Cut Line= 3
     1596472.802      275491.131     1596706.113      275766.457
     1596845.002      275860.207
#Sta/Elev= 30
       0  923.78    19.5  914.29    29.3  909.11      39  903.63    58.5  892.24
    68.3  886.77      78  881.69    97.5  872.68   107.3  868.44   126.8  860.56
   136.6  857.18   146.3  854.59   156.1  852.68   165.8   851.3   175.6  850.58
   224.3  849.95   302.4  850.61   320.4  850.33   331.6  850.62   341.4   852.9
   351.1  858.15   360.9  863.11   379.5  870.15   388.8   873.9   398.1  878.06
     426  891.09     454  903.78   463.3  908.24   472.6  912.94   528.4  942.23
#Mann= 3 , 0 , 0
       0     .06       0   320.4    .045       0   331.6      .1       0
Bank Sta=320.4,331.6
XS Rating Curve= 0 ,0
Exp/Cntr=0.3,0.1

Type RM Length L Ch R = 1 ,9322.3  ,454.7,437.7,418.9
XS GIS Cut Line= 3
     1595975.487      275714.943     1596253.173      275881.245
     1596687.384      276088.306
#Sta/Elev= 30
       0  966.19      49  942.63    58.8  938.48   117.7  917.35   166.7  900.27
   196.2  890.42     206  887.35   225.6  881.79     255  874.17   264.8  871.93
   284.4  868.36   304.1  864.29   323.7     861   343.3  858.78   362.9  857.03
   392.4  855.13   470.9  851.51   480.8  851.18   529.8  850.44   539.7  849.77
   549.5  848.73   559.3  848.08   569.1  849.55   578.9  852.09   618.2  863.78
     628  867.46   677.1  889.65   745.8  920.21   765.5  929.31   804.7  948.18
#Mann= 3 , 0 , 0
       0     .06       0   549.5    .045       0   569.1      .1       0
Bank Sta=549.5,569.1
XS Rating Curve= 0 ,0
Exp/Cntr=0.3,0.1

Type RM Length L Ch R = 1 ,8884.7  ,292.7,284.7,278
XS GIS Cut Line= 2
     1596011.864      276495.819     1596691.552      276219.777
#Sta/Elev= 30
       0  954.28    97.8  917.77   127.2  906.52   156.5  895.01   195.6  879.22
   215.2  871.55   244.5  860.76   254.3   857.5   264.1  855.14   273.9  853.68
   283.7  852.66   342.4  847.82     401  844.06   410.8  843.38   420.6   843.1
   430.4  843.42   459.7  845.84   479.3  847.22   498.8  849.15   508.6   850.5
   518.4  852.66   528.2  856.42     538  861.47   567.3  878.02   606.4  899.82
   635.8  915.49   665.1   930.4   674.9   935.2     714  953.73   733.6  962.69
#Mann= 3 , 0 , 0
       0     .06       0     401    .045       0   430.4      .1       0
Bank Sta=401,430.4
XS Rating Curve= 0 ,0
Exp/Cntr=0.3,0.1

Type RM Length L Ch R = 1 ,8600    ,130.8,129.5,128.7
XS GIS Cut Line= 2
     1596417.919      276660.554     1596800.927      276402.069
#Sta/Elev= 22
       0  859.74    68.8  854.05    78.6  853.16    98.3  851.15     118   848.7
   127.8  847.61   137.6   846.7   147.5  845.86     177  843.84   196.6  841.96
   206.5  841.87   216.3  843.18   226.1  845.74     236  849.68   245.8  855.73
   265.4  869.66   275.3   876.5   285.1  882.99   294.9  888.53   363.8  920.22
   403.1  938.79   462.1  966.97
#Mann= 3 , 0 , 0
       0     .06       0   196.6    .045       0   216.3      .1       0
Bank Sta=196.6,216.3
XS Rating Curve= 0 ,0
Exp/Cntr=0.3,0.1

Type RM Length L Ch R = 1 ,8470.5  ,218.4,213.4,207.8
XS GIS Cut Line= 3
      1596435.28      276865.415      1596566.52      276715.878
       1596801.6      276554.651
#Sta/Elev= 30
       0  909.67    28.4  898.08    47.4  889.88    56.8  885.38    75.8  874.88
    85.3  869.86    94.7  865.39   104.2  861.73   113.7   858.7   123.2  856.26
   132.6  854.39   142.1  853.31   151.6  853.12   161.1  853.14     180  851.52
     199  850.45   267.8  844.43   287.4  842.33   297.3  841.42   307.1  841.29
   316.9  842.13   326.7  843.91   336.6  846.06   346.4     849   356.2   854.1
   395.6  879.54   405.4   885.4   415.2  890.24     425  894.56     484  919.89
#Mann= 3 , 0 , 0
       0     .06       0   297.3    .045       0   316.9      .1       0
Bank Sta=297.3,316.9
XS Rating Curve= 0 ,0
Exp/Cntr=0.3,0.1

Type RM Length L Ch R = 1 ,8257.1  ,290.1,288.5,286.9
XS GIS Cut Line= 2
     1596545.719      277097.381     1597001.448      276558.319
#Sta/Elev= 30
       0  962.99    68.6   931.3   186.3  877.43   205.9  868.57   215.7  864.58
   225.5  861.39   235.3  858.96   254.9  854.87   274.5  851.18   294.1  848.06
   313.7  845.37   333.3  843.03   362.8  839.72   364.8  839.61   372.6  839.16
   379.8  839.63   382.4   839.8   411.8  844.15   421.6  846.44   431.4     851
   441.2  856.88     451  863.19   460.8  868.53   480.4  877.88     500  888.14
   509.8  892.36   558.8  912.18   647.1  946.68   666.7  954.06   705.9  967.74
#Mann= 3 , 0 , 0
       0     .06       0   364.8    .045       0   379.8     .06       0
Bank Sta=364.8,379.8
XS Rating Curve= 0 ,0
Exp/Cntr=0.3,0.1

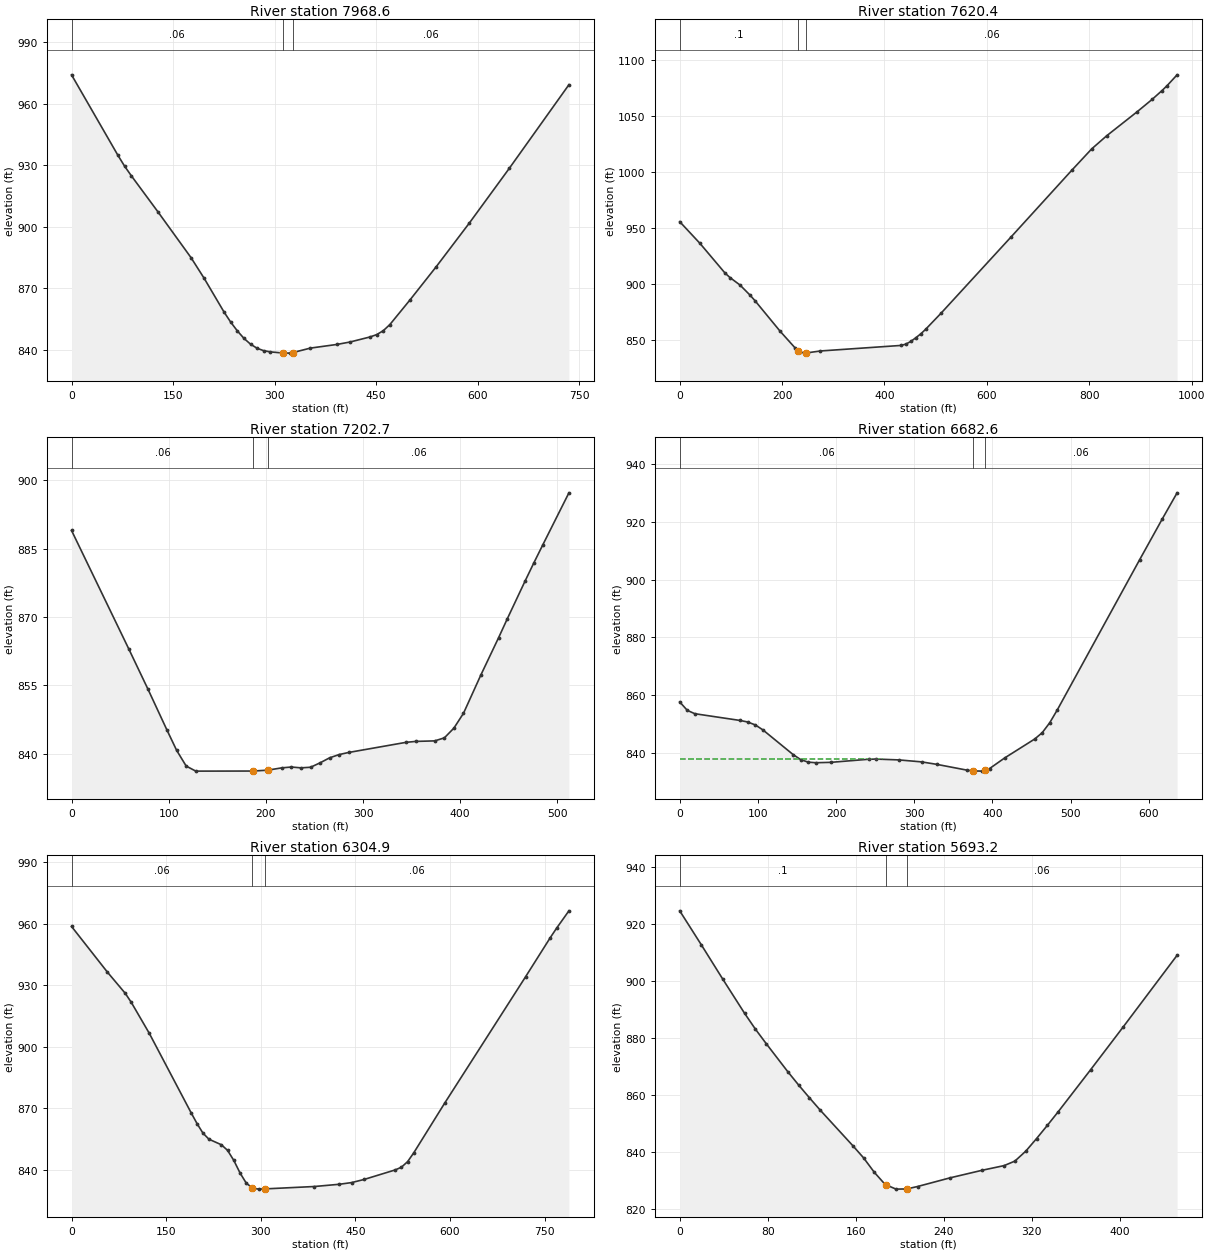
Type RM Length L Ch R = 1 ,7968.6  ,347.3,348.2,349
XS GIS Cut Line= 2
     1596766.639        277276.7     1597226.708      276703.783
#Sta/Elev= 30
       0  974.01    68.6  934.77    78.4  929.52    88.2  924.91   127.4   907.4
   176.4  885.04   195.9  874.93   225.3  858.49   235.1   853.6   244.9  849.33
   254.7  845.67   264.5  842.82   274.3  840.82   284.1  839.64   293.9  839.08
   312.3  838.54   323.3  838.48   327.3  838.77   352.7  840.92   391.9   842.7
   411.5   843.9   440.9  846.35   450.7  847.48   460.5  849.39   470.3   852.4
   499.6  864.22   538.8  880.58   587.8  901.88   646.6  928.42   734.8  969.19
#Mann= 3 , 0 , 0
       0     .06       0   312.3    .045       0   327.3     .06       0
Bank Sta=312.3,327.3
XS Rating Curve= 0 ,0
Exp/Cntr=0.3,0.1

Type RM Length L Ch R = 1 ,7620.4  ,405.3,417.7,429.4
XS GIS Cut Line= 2
      1597040.51      277478.458     1597642.073      276715.437
#Sta/Elev= 30
       0   955.6    39.3  936.27    88.3  909.66    98.2  905.52   117.8  898.81
   137.4  889.76   147.2  884.71   196.3  857.34   225.7  842.33   231.9  840.07
   235.6  838.72   245.4  837.82   246.9  837.95   274.8  839.75   431.8   844.7
   441.6  845.85   451.5  848.32   461.3  851.64   471.1  855.16   480.9  859.42
   510.4  873.54   647.8  942.18   765.5 1001.47   804.8 1020.82   834.2 1032.61
   893.1 1053.91   922.6 1065.06   942.2 1073.08     952 1077.45   971.6 1087.16
#Mann= 3 , 0 , 0
       0      .1       0   231.9    .045       0   246.9     .06       0
Bank Sta=231.9,246.9
XS Rating Curve= 0 ,0
Exp/Cntr=0.3,0.1

Type RM Length L Ch R = 1 ,7202.7  ,509.6,520.1,530.5
XS GIS Cut Line= 3
     1597320.697      277580.693     1597697.129      277435.807
     1597763.405       277349.79
#Sta/Elev= 30
       0  889.02      59  862.98    78.7  854.17    98.4  845.13   108.2  840.75
     118  837.31   127.9   836.2   186.9  836.22   201.9  836.41   216.4  836.92
   226.3   837.1   236.1  836.92     246  837.05   255.8  838.02   265.6  839.12
   275.5  839.84   285.3   840.3   344.3  842.52   354.2  842.72   373.8  842.84
   383.7   843.5   393.5  845.63   403.4   848.9   421.4  857.36   439.6  865.52
   448.6  869.69   466.7  877.88   475.7  881.86   484.8  885.77   511.9  897.28
#Mann= 3 , 0 , 0
       0     .06       0   186.9    .045       0   201.9     .06       0
Bank Sta=186.9,201.9
XS Rating Curve= 0 ,0
Exp/Cntr=0.3,0.1

Type RM Length L Ch R = 1 ,6682.6  ,369.8,377.8,392.4
XS GIS Cut Line= 3
     1597367.572      277898.401     1597792.919      277898.401
     1597987.363      277979.998
#Sta/Elev= 30
       0   857.7     9.7  854.78    19.3  853.62    77.3  851.28      87  850.75
    96.7  849.73   106.3  848.04     145  839.49   154.7  837.74   164.3  836.86
     174  836.66   193.3  836.79   241.7  837.86   251.3  837.92   280.3  837.63
   309.3  836.95   328.7   836.1   367.4  834.09   375.2  833.84   386.7  833.75
   390.2  834.07   396.4  834.65   415.7  838.32   454.1  844.87   463.7  847.06
   473.3   850.5   482.9  854.91   588.3  906.91     617   920.9   636.2  930.05
#Mann= 3 , 0 , 0
       0     .06       0   375.2    .045       0   390.2     .06       0
#XS Ineff= 2 , 0
          260.28  838.02
Permanent Ineff=
       F       F
Bank Sta=375.2,390.2
XS Rating Curve= 0 ,0
Exp/Cntr=0.3,0.1

Type RM Length L Ch R = 1 ,6304.9  ,612.1,611.7,602.3
XS GIS Cut Line= 3
     1597188.948      278094.777     1597399.885       278040.09
     1597938.948       278227.59
#Sta/Elev= 30
       0  958.77    56.8  936.52    85.3  926.11    94.7  921.76   123.2  906.69
   189.5  867.96     199  862.61   208.4  857.96   217.9     855   237.6   852.3
   247.4  849.56   257.3  844.66   267.1  838.58     277  833.59   286.8   831.2
   296.6  830.66   306.5  830.77   385.2  831.94   424.6  833.03   444.2  833.86
   463.9  835.38   513.1  840.02     523  841.34   532.8  844.05   542.6  848.37
   591.8  872.69   719.8   934.2   759.1  953.34     769   957.9   788.6  966.39
#Mann= 3 , 0 , 0
       0     .06       0   286.8    .045       0   306.5     .06       0
Bank Sta=286.8,306.5
XS Rating Curve= 0 ,0
Exp/Cntr=0.3,0.1

Type RM Length L Ch R = 1 ,5693.2  ,409,408.1,407.4
XS GIS Cut Line= 2
     1597201.969      278441.131     1597626.448      278597.381
#Sta/Elev= 29
       0  924.63    19.7  912.66    39.3  900.55      59  888.63    68.8  883.09
    78.7  877.96    98.3  868.12   108.2  863.41     118  858.94   127.8  854.61
   157.3  842.18   167.2  837.86     177  832.76   186.8  828.52   187.6  828.39
   196.7  826.88   206.5  826.95   216.3   827.8   245.8  830.84   275.3  833.53
     295  835.14   304.8  836.73   314.7  840.22   324.5  844.64   334.3  849.27
   344.2  854.07   373.7  868.84   403.2  883.81   452.3  909.02
#Mann= 3 , 0 , 0
       0      .1       0   187.6    .045       0   206.5     .06       0
Bank Sta=187.6,206.5
XS Rating Curve= 0 ,0
Exp/Cntr=0.3,0.1

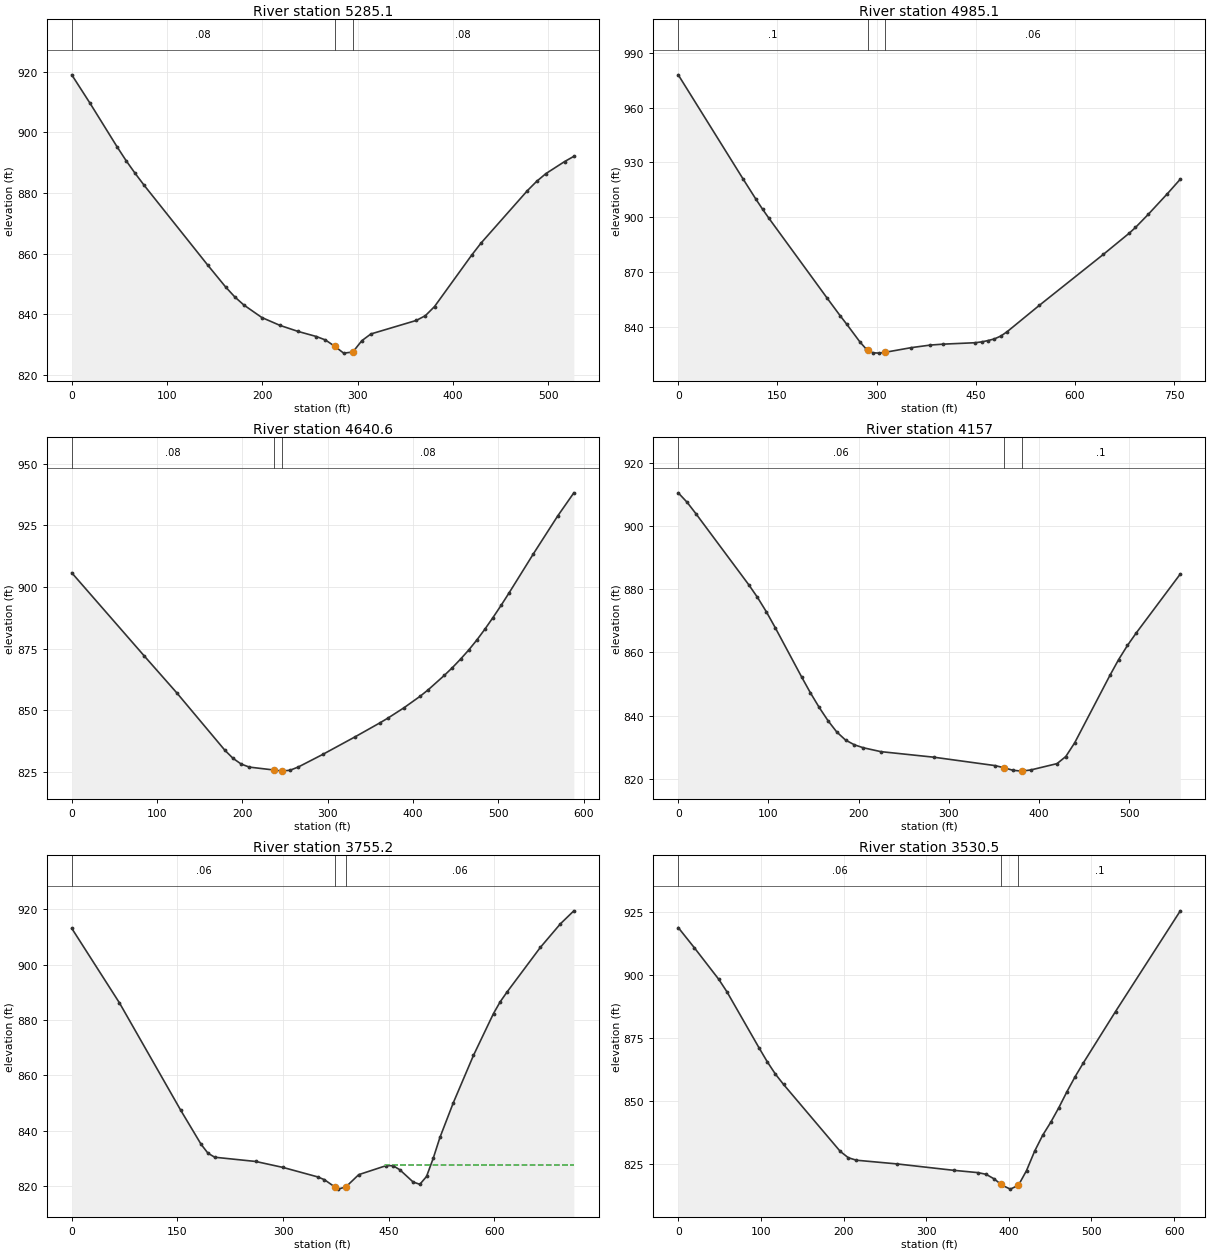
Type RM Length L Ch R = 1 ,5285.1  ,319.6,300,281.7
XS GIS Cut Line= 4
     1597024.885      278691.131     1597142.073       278852.59
     1597313.948      278909.881     1597459.781      278899.465
#Sta/Elev= 30
       0  918.95      19  909.66    47.5  895.23      57  890.65    66.5  886.45
      76  882.49   142.5  856.25   161.5  848.95     171  845.71   180.5  843.04
   199.5  838.88   218.6  836.28   237.6  834.29   256.7  832.62   266.2  831.48
   275.9  829.42   285.3  827.14   294.9  827.49   304.4  831.24   313.9  833.46
   361.6  837.93   371.1   839.5   380.7  842.51   419.7  859.48   429.4  863.41
   478.2  880.76   487.9  883.82   497.6  886.37   517.1  890.32   526.9  892.06
#Mann= 3 , 0 , 0
       0     .08       0   275.9    .045       0   294.9     .08       0
Bank Sta=275.9,294.9
XS Rating Curve= 0 ,0
Exp/Cntr=0.3,0.1

Type RM Length L Ch R = 1 ,4985.1  ,341.7,344.4,347.3
XS GIS Cut Line= 3
     1596983.219      279370.819     1597186.344      279185.923
      1597617.53       278964.68
#Sta/Elev= 30
       0  977.94    98.1  920.98   117.7  909.81   127.5  904.49   137.3  899.43
   225.6  855.64   245.2  846.06   255.1  841.44   274.7  831.92   284.4  827.94
   287.3  827.35   294.1  825.96   303.8  825.76   313.4  826.24   352.2  828.75
   381.3  830.17   400.7  830.67   449.1  831.45   458.8  831.91   468.5  832.62
   478.2  833.55   487.9  835.11   497.6  837.53   546.1  851.89     643  879.78
   681.8  891.27   691.5  894.47   710.8  901.64   739.9  912.99   759.3  920.89
#Mann= 3 , 0 , 0
       0      .1       0   287.3    .045       0   313.4     .06       0
Bank Sta=287.3,313.4
XS Rating Curve= 0 ,0
Exp/Cntr=0.3,0.1

Type RM Length L Ch R = 1 ,4640.6  ,481.6,483.6,484.3
XS GIS Cut Line= 4
     1597241.031      279456.756     1597423.323      279407.277
     1597560.909      279340.502     1597803.336      279295.971
#Sta/Elev= 30
       0  905.77      85     872   122.8  857.15   179.4  833.75   188.9  830.49
   198.4  828.17     208  826.92   236.7  825.74     246  825.28   255.8  825.65
   265.4  826.95     294  832.05   332.3  839.26   360.8  844.82   370.3  846.77
   389.2  850.98   408.2  855.67   417.7  858.31   436.6  864.16   446.1  867.32
   455.6  870.76   465.1  874.43   474.5  878.44     484  882.86   493.5  887.59
     503  892.52   512.5  897.67   540.9  913.48   569.3   928.8   588.3  938.23
#Mann= 3 , 0 , 0
       0     .08       0   236.7    .045       0     246     .08       0
Bank Sta=236.7,246
XS Rating Curve= 0 ,0
Exp/Cntr=0.3,0.1

Type RM Length L Ch R = 1 ,4157    ,398.7,401.8,404.7
XS GIS Cut Line= 2
      1597281.84       279926.21     1597807.327      279742.044
#Sta/Elev= 30
       0  910.61     9.8  907.63    19.5  904.04    78.2  881.47    87.9  877.46
    97.7  872.91   107.5   867.9   136.8  852.26   146.5  847.25   156.3  842.59
   166.1  838.37   175.8  834.79   185.6  832.22   195.4  830.72   205.2  829.79
   224.7  828.56   283.3   826.8   351.7  824.12   361.4  823.43   371.2  822.65
     381  822.38   390.8  822.74   420.1  824.76   429.8  827.01   439.6  831.33
   478.7  852.72   488.4  857.75   498.2  862.23     508  866.22   556.8  884.88
#Mann= 3 , 0 , 0
       0     .06       0   361.4    .045       0     381      .1       0
Bank Sta=361.4,381
XS Rating Curve= 0 ,0
Exp/Cntr=0.3,0.1

Type RM Length L Ch R = 1 ,3755.2  ,217.3,224.7,232
XS GIS Cut Line= 4
     1597402.294      280243.887     1597621.044      280203.957
     1597850.211      280157.082      1598103.01      280201.548
#Sta/Elev= 30
       0  913.15    67.7  886.22   154.7  847.42   183.7  835.08   193.4  831.89
     203  830.43   261.4  828.89   300.3  826.72   349.1  823.33   358.8  822.31
   374.4  819.54   378.3   818.9   389.4  819.73   407.5  824.13   446.5  827.39
   456.3  827.36   465.8  825.91   484.8  821.47   494.3  820.64   503.8  823.47
   513.3  830.04   522.8  837.56   541.8   850.1   570.4   867.2   598.9  882.37
   608.4   886.6   617.9  890.06   665.4  906.25   693.9  914.78     713  919.48
#Mann= 3 , 0 , 0
       0     .06       0   374.4    .045       0   389.4     .06       0
#XS Ineff= 2 , 0
                          445.07          827.44
Permanent Ineff=
       F       F
Bank Sta=374.4,389.4
XS Rating Curve= 0 ,0
Exp/Cntr=0.3,0.1

Type RM Length L Ch R = 1 ,3530.5  ,126.8,129.8,133.1
XS GIS Cut Line= 2
     1597430.701      280343.106        1598034.      280414.721
#Sta/Elev= 30
       0  918.96    19.6  910.88      49  898.37    58.8  893.46      98  870.95
   107.8  865.49   117.6  860.62   127.4  856.52     196  829.87   205.8  827.33
   215.6  826.34   264.6  824.87   333.2  822.32   362.6   821.4   372.4  820.74
   382.2  818.92   390.3   816.8     392  816.36   401.8  814.83   411.6  816.35
   421.4   822.2   431.2  829.92     441   836.3   450.8  841.49   460.6  847.32
   470.4  853.67   480.2  859.58     490  864.99   529.1  885.53   607.5  925.62
#Mann= 3 , 0 , 0
       0     .06       0   390.3    .045       0   411.6      .1       0
Bank Sta=390.3,411.6
XS Rating Curve= 0 ,0
Exp/Cntr=0.3,0.1

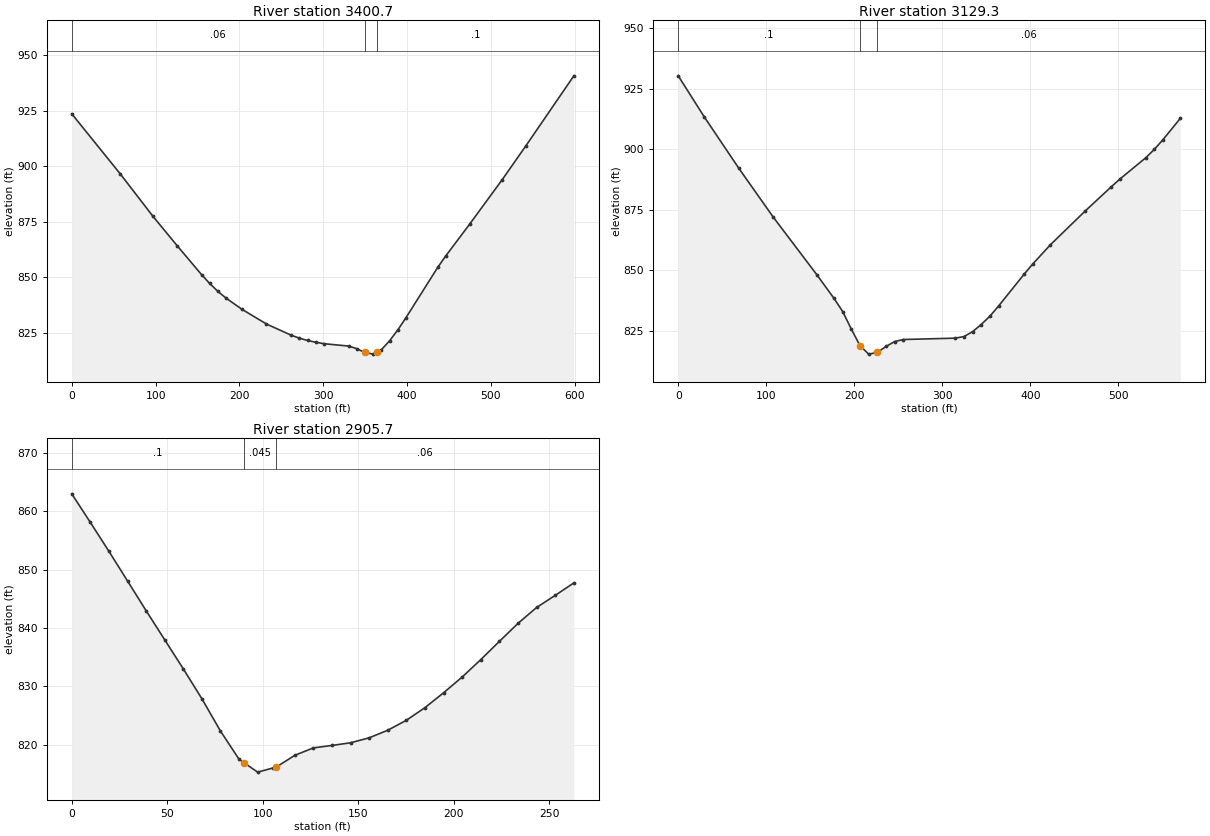
Type RM Length L Ch R = 1 ,3400.7  ,271.8,271.4,270.3
XS GIS Cut Line= 4
     1597432.871      280475.484     1597665.076      280479.825
     1597816.773      280519.901     1598022.086      280563.332
#Sta/Elev= 30
       0   923.7    58.1  896.52    96.8  877.55   125.8  864.24   154.8  851.27
   164.5  847.28   174.2  843.75   183.9  840.71   203.2  835.59   232.2  829.02
   261.7  823.97   271.5  822.63   281.3  821.58   291.1  820.78   300.9  820.13
   330.3  819.06   340.1  817.89   349.4  816.18   359.7  815.43   364.4   816.4
   369.5  817.46   379.3   821.5   389.2  826.46   398.7  831.83   436.8  854.64
   446.4  859.78     475  874.16   513.2  893.85   541.8  909.29     599  940.82
#Mann= 3 , 0 , 0
       0     .06       0   349.4    .045       0   364.4      .1       0
Bank Sta=349.4,364.4
XS Rating Curve= 0 ,0
Exp/Cntr=0.3,0.1

Type RM Length L Ch R = 1 ,3129.3  ,223.4,223.6,223.8
XS GIS Cut Line= 2
     1597421.894       280677.31     1597976.947      280808.123
#Sta/Elev= 30
       0  930.34    29.5  913.41    68.8  892.14   108.2  871.81   157.3   848.2
     177  838.33   186.8  832.92   196.6  825.67   206.5   818.8   216.3  815.32
   226.1     816     236  818.48   245.8  820.52   255.6  821.36   314.6  821.92
   324.5  822.59   334.3  824.59   344.1  827.56     354  830.99   363.8  835.17
   393.3  848.54   403.1  852.74   422.8  860.54   462.1  874.42   491.6  884.38
   501.4   887.6   530.9  896.43   540.8  899.96   550.6  903.95   570.3  912.76
#Mann= 3 , 0 , 0
       0      .1       0   206.5    .045       0   226.1     .06       0
Bank Sta=206.5,226.1
XS Rating Curve= 0 ,0
Exp/Cntr=0.3,0.1

Type RM Length L Ch R = 1 ,2905.7  ,81.9,81.2,80.6
XS GIS Cut Line= 2
     1597485.627      280920.971     1597740.836      280983.471
#Sta/Elev= 30
       0  862.98     9.7   858.1    19.5  853.11    29.2  848.05    38.9  842.98
    48.7  837.96    58.4     833    68.1   827.9    77.8  822.38    87.6  817.52
    90.2  816.93    97.3  815.33   105.2  816.03     107  816.19   116.8  818.22
   126.5  819.48   136.2   819.9     146  820.36   155.7  821.21   165.4   822.5
   175.2  824.22   184.9  826.38   194.6  828.91   204.4  831.63   214.1   834.6
   223.8  837.71   233.6  840.81   243.3  843.52     253  845.58   262.8  847.73
#Mann= 3 , 0 , 0
       0      .1       0    90.2    .045       0     107     .06       0
Bank Sta=90.2,107
XS Rating Curve= 0 ,0
Exp/Cntr=0.3,0.1