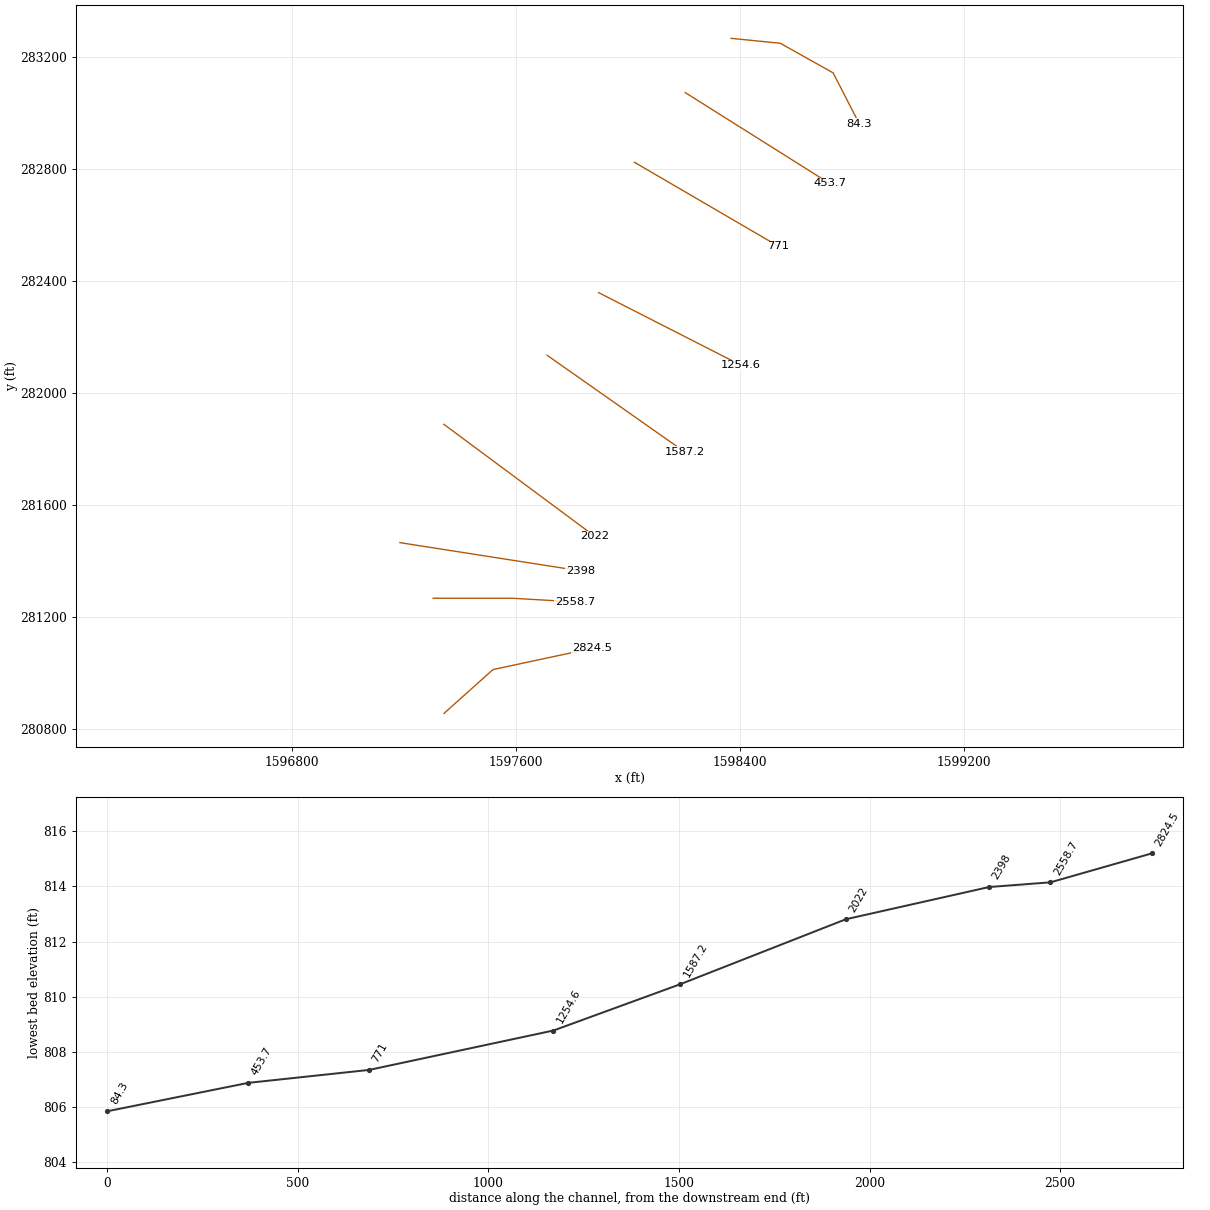
HEC-RAS study RFKRNLDCK.prj: RFKRNLDCK

--- RFKRNLDCK.g01 (geometry) --- (continued)

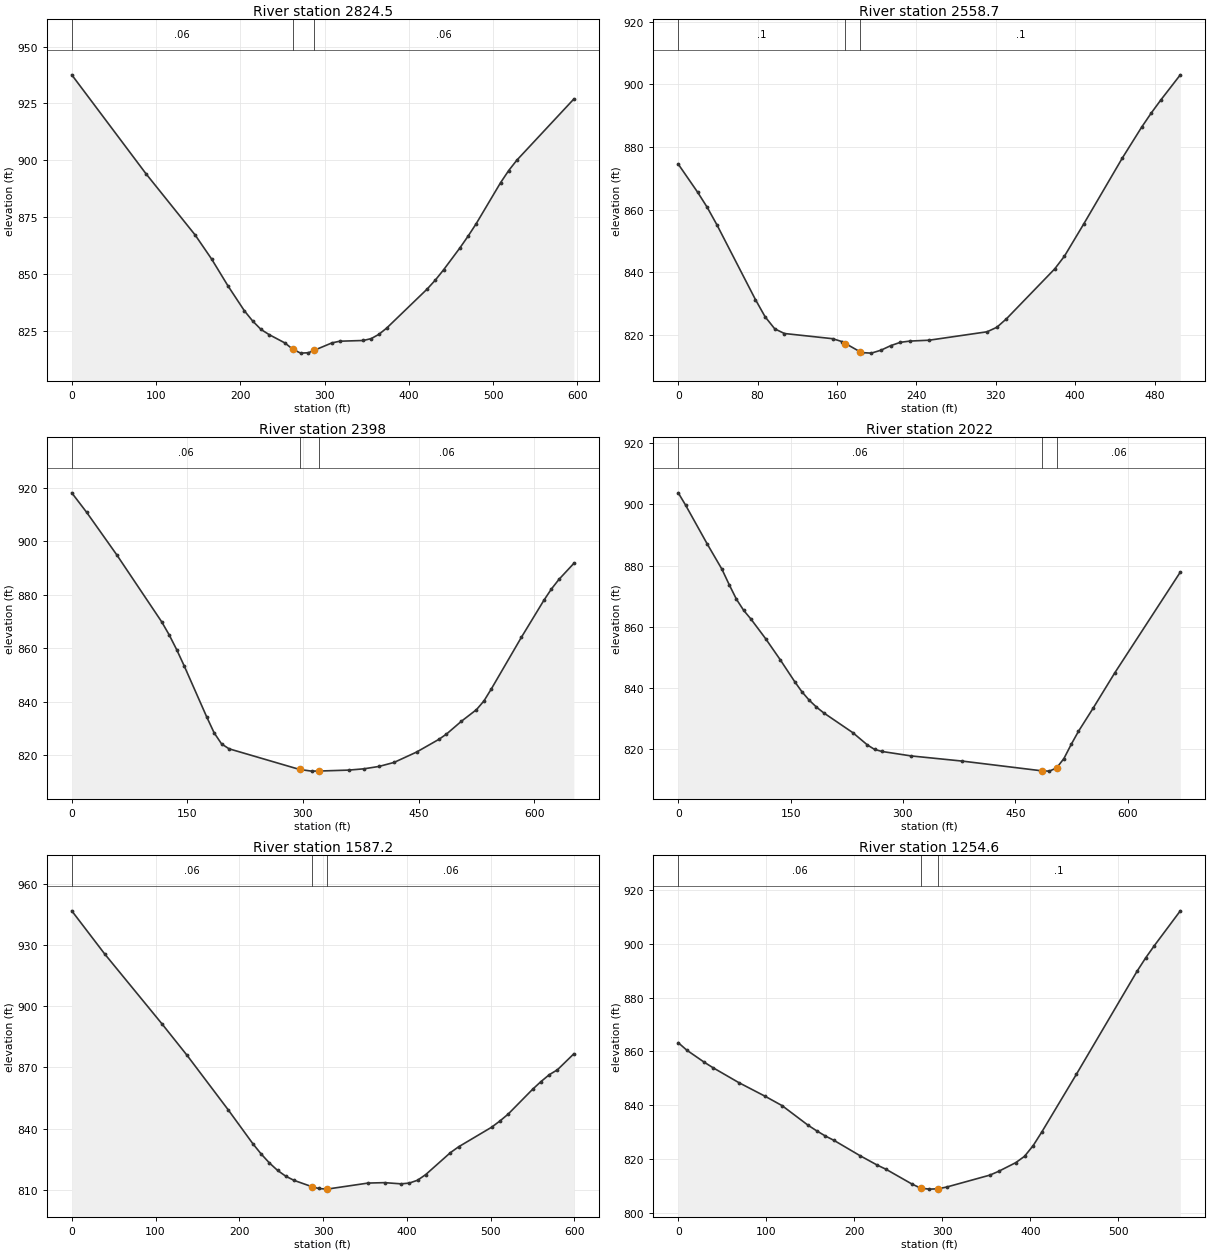
Type RM Length L Ch R = 1 ,2824.5  ,270.7,265.8,261
XS GIS Cut Line= 4
     1597342.898      280857.388     1597517.507      281013.679
     1597663.058      281044.929     1597871.044      281089.373
#Sta/Elev= 30
       0  937.56    87.9  894.16   146.5  867.11     166  856.56   185.5   844.7
     205  833.75   214.8  829.28   224.6  825.61   234.3  823.33     253  819.67
   262.2  816.95   271.6   815.2   280.9  815.37   287.9  816.47   308.8   819.7
   318.1  820.44     346  820.76   355.3  821.57   364.6  823.48   373.9  826.26
   421.9  843.41   431.5  847.32   441.2  851.78   460.6  861.43   470.2  866.54
   479.9  872.05   508.9  890.12   518.6  895.49   528.2  900.02   595.9  926.93
#Mann= 3 , 0 , 0
       0     .06       0   262.2    .045       0   287.9     .06       0
Bank Sta=262.2,287.9
XS Rating Curve= 0 ,0
Exp/Cntr=0.3,0.1

Type RM Length L Ch R = 1 ,2558.7  ,164.2,160.8,156.3
XS GIS Cut Line= 3
      1597304.03      281268.511     1597586.148      281268.511
     1597809.672       281255.49
#Sta/Elev= 30
       0  874.54    19.5  865.58    29.2  860.73    38.9  855.19    77.8  831.26
    87.6  825.74    97.3   821.9     107  820.42   155.6  818.76   165.4   817.8
   168.5  817.22   183.5  814.54   184.8  814.32   194.6  814.15   204.3  815.08
     214  816.52   223.8   817.6   233.5     818   252.9  818.28   311.3  820.97
   321.1  822.41   330.8  825.12   379.5  841.09   389.2  845.12   408.7  855.43
   447.6   876.5   467.1  886.37   476.8   890.9   486.6  895.13     506  903.06
#Mann= 3 , 0 , 0
       0      .1       0   168.5    .045       0   183.5      .1       0
Bank Sta=168.5,183.5
XS Rating Curve= 0 ,0
Exp/Cntr=0.3,0.1

Type RM Length L Ch R = 1 ,2398    ,386.6,376,365.1
XS GIS Cut Line= 2
     1597185.494      281466.987     1597829.308      281366.391
#Sta/Elev= 30
       0  918.14    19.4  910.81    58.4  894.93   116.7  869.86   126.4  864.99
   136.2  859.42   145.9  853.38   175.1  834.29   184.8   828.3   194.5  824.14
   204.2  822.33   295.6  814.61   311.2  813.98     321  814.01   359.8  814.37
   379.3  814.85   398.8  815.74   418.2  817.23   447.4   821.1   476.6   825.9
   486.3  827.85   505.7  832.65   525.2  836.98   534.9  840.24   544.6  844.79
   583.5  864.06   612.7  877.91   622.4  882.11   632.2  885.72   651.6  891.74
#Mann= 3 , 0 , 0
       0     .06       0   295.6    .045       0     321     .06       0
Bank Sta=295.6,321
XS Rating Curve= 0 ,0
Exp/Cntr=0.3,0.1

Type RM Length L Ch R = 1 ,2022    ,432.7,434.8,433.9
XS GIS Cut Line= 2
     1597342.225      281889.605     1597880.419      281490.299
#Sta/Elev= 30
       0  903.77     9.7   899.8    38.8  887.01    58.3  878.82      68  873.77
    77.7  868.99    87.4  865.34    97.1   862.5   116.6  856.12     136  849.27
   155.4  842.08   165.1  838.75   174.8     836   184.5  833.74   194.2  831.85
   233.1  825.37   252.5  821.37   262.2  819.89   271.9  819.24   310.8  817.78
   378.8   816.1   485.6   812.9   495.3  812.81     505  813.84   514.8  816.91
   524.5  821.52   534.2   825.8   553.6   833.3   582.7  844.92   670.2  877.86
#Mann= 3 , 0 , 0
       0     .06       0   485.6    .045       0     505     .06       0
Bank Sta=485.6,505
XS Rating Curve= 0 ,0
Exp/Cntr=0.3,0.1

Type RM Length L Ch R = 1 ,1587.2  ,329.4,332.6,335.9
XS GIS Cut Line= 2
     1597711.107       282135.95     1598201.512      281791.409
#Sta/Elev= 30
       0  946.66    39.3  925.55   108.1  891.12   137.6  875.95   186.7  849.28
   216.2  832.65     226  827.69   235.8  823.31   245.6  819.64   255.5  816.75
   265.3  814.74   286.9  811.61   294.8  810.76   304.6  810.45   353.7  813.42
   373.4  813.62     393  813.04   402.8  813.39   412.7   814.8   422.5  817.57
     452  828.32   461.8  831.18   501.1  840.74   510.9  843.75   520.7  847.09
   550.2  859.37     560  863.07   569.9  866.43   579.7  868.86   599.3  876.68
#Mann= 3 , 0 , 0
       0     .06       0   286.9    .045       0   304.6     .06       0
Bank Sta=286.9,304.6
XS Rating Curve= 0 ,0
Exp/Cntr=0.3,0.1

Type RM Length L Ch R = 1 ,1254.6  ,484.3,483.6,482.4
XS GIS Cut Line= 2
     1597894.695      282359.775     1598402.704      282100.741
#Sta/Elev= 30
       0  863.22     9.8  860.43    29.5  855.97    39.3  853.96    68.8  848.38
    98.3  843.37     118  839.81   147.5  832.52   157.3  830.44   167.1  828.52
     177  826.88   206.5   821.2   226.1  817.69     236  816.15   265.5  810.65
   275.3  809.14   285.1  808.77     295  808.89   304.8  809.54   353.9  813.98
   363.8  815.38   383.4  818.63   393.3  820.98   403.1  824.96   412.9  830.02
   452.3  851.55   521.1  889.81   530.9  894.78   540.7  899.31   570.2  912.26
#Mann= 3 , 0 , 0
       0     .06       0   275.3    .045       0     295      .1       0
Bank Sta=275.3,295
XS Rating Curve= 0 ,0
Exp/Cntr=0.3,0.1

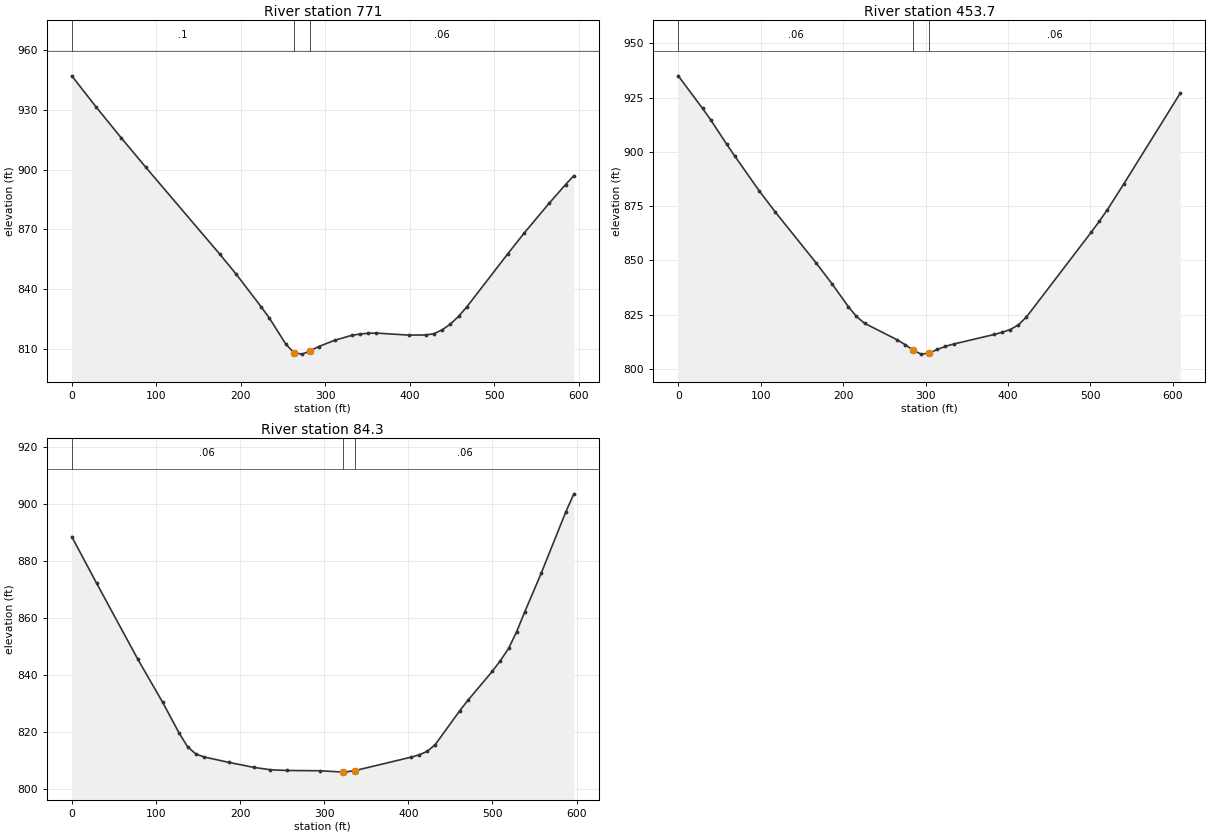
Type RM Length L Ch R = 1 ,771     ,317.9,317.3,316.5
XS GIS Cut Line= 2
     1598022.955      282825.031     1598535.994      282525.759
#Sta/Elev= 30
       0  947.06    29.2  931.22    58.4  915.98    87.6  901.14   175.3  857.42
   194.7   847.4     224  831.14   233.7  825.52   253.2   812.4   262.9  808.03
   272.6  807.34   282.4  809.04   292.1  811.14   311.6  814.38     331  816.74
   340.8  817.42   350.5  817.81   360.3  817.91   399.2  816.88   418.7  816.96
   428.4  817.58   438.2  819.53   447.9  822.41   457.6  826.31   467.4  831.08
     516  857.79   535.5  868.25   564.7  883.04   584.2  892.48     594  896.94
#Mann= 3 , 0 , 0
       0      .1       0   262.9    .045       0   282.4     .06       0
Bank Sta=262.9,282.4
XS Rating Curve= 0 ,0
Exp/Cntr=0.3,0.1

Type RM Length L Ch R = 1 ,453.7   ,373.9,369.5,369.4
XS GIS Cut Line= 2
     1598204.027      283074.006     1598719.581      282749.584
#Sta/Elev= 30
       0  935.01    29.5     920    39.3  914.79      59  903.41    68.8  897.95
    98.2  882.07   117.9  872.24     167  849.01   186.7  839.18   206.3  828.77
   216.1  824.22     226  821.08   265.3  813.52   275.1  811.26   284.9  808.68
   294.7  806.87   304.6  807.35   314.4  809.05   324.2  810.46     334   811.5
   383.2  815.91     393  816.93   402.8   818.2   412.6  820.31   422.5     824
   501.1  863.05   510.9  868.07   520.7  873.42   540.4  885.15   609.1  927.06
#Mann= 3 , 0 , 0
       0     .06       0   284.9    .045       0   304.6     .06       0
Bank Sta=284.9,304.6
XS Rating Curve= 0 ,0
Exp/Cntr=0.3,0.1

Type RM Length L Ch R = 1 ,84.3    ,75.3,84.3,88.7
XS GIS Cut Line= 4
     1598367.495      283267.653     1598543.538      283250.049
     1598732.155      283144.423     1598825.207      282963.351
#Sta/Elev= 30
       0  888.39    29.5  872.08    78.6  845.36   108.1  830.28   127.8  819.42
   137.6  814.78   147.4   812.2   157.3  811.16   186.8  809.25   216.2  807.51
   235.9  806.68   255.5  806.42   294.8  806.32   321.9  805.87   324.3  805.84
   336.9   806.4   402.8  811.05   412.5  811.88   422.2  813.09   431.9  815.46
     461  827.32   470.6  830.96   499.7  841.14   509.4  844.93   519.1  849.19
   528.8  855.13   538.5  862.12   557.9  875.56     587  896.98   596.7  903.41
#Mann= 3 , 0 , 0
       0     .06       0   321.9    .045       0   336.9     .06       0
Bank Sta=321.9,336.9
XS Rating Curve= 0 ,0
Exp/Cntr=0.3,0.1

Chan Stop Cuts=-1
Use User Specified Reach Order=0
Composite Channel Slope=5